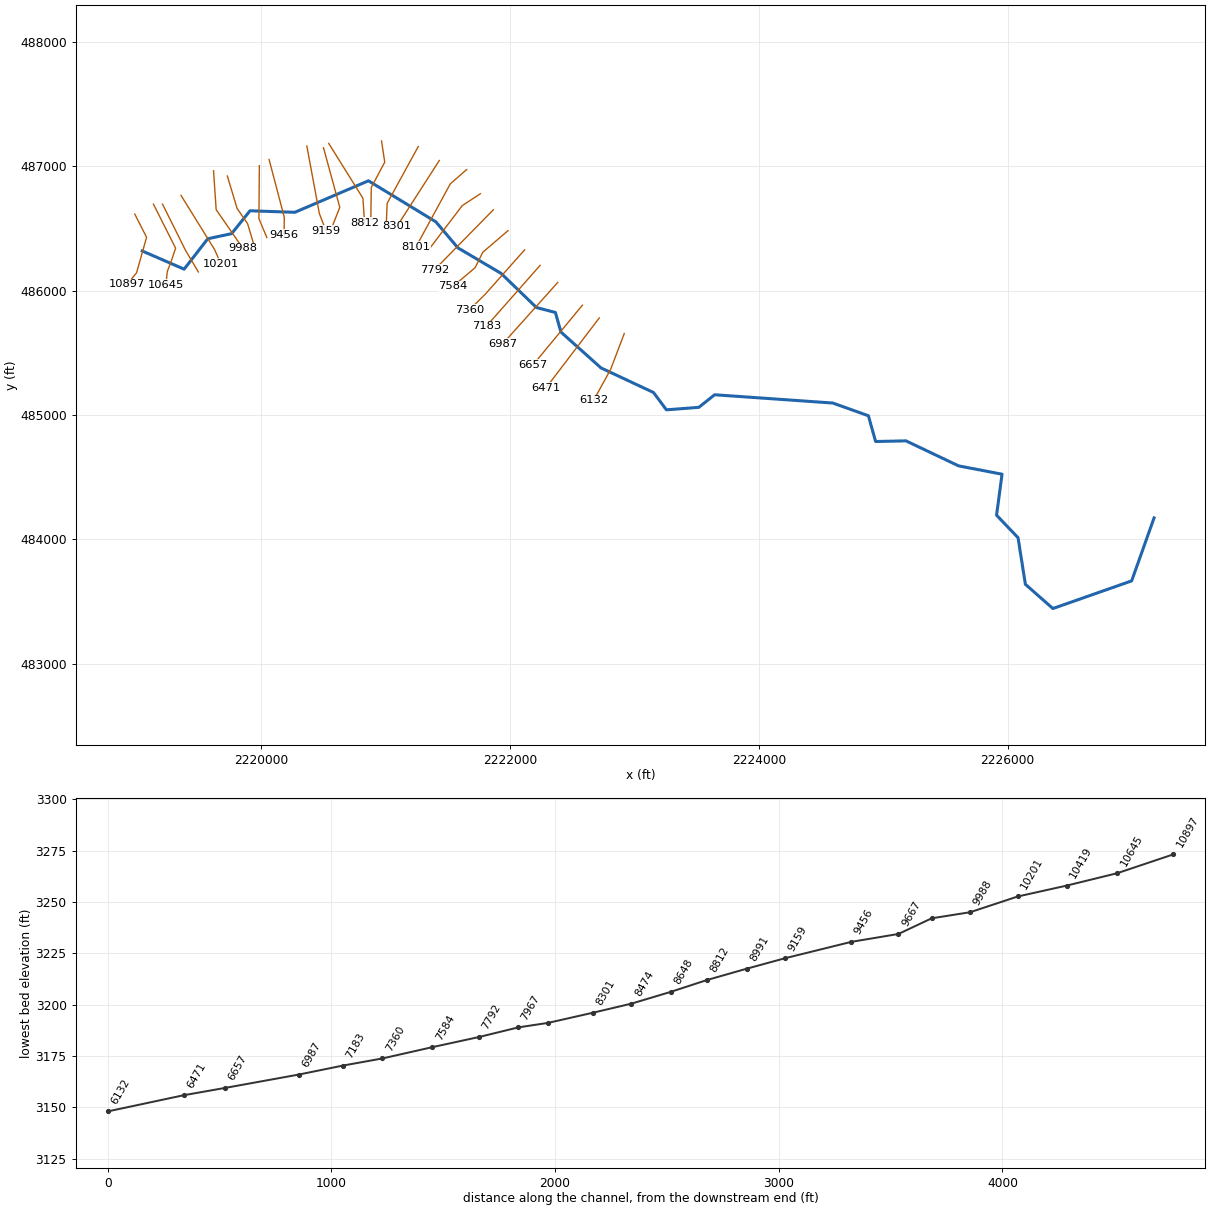
--- CRKDFK.prj (project) ---

Proj Title=CRKDFK
Current Plan=p01
Default Exp/Contr=0,0
English Units
Geom File=g01
Flow File=f01
Plan File=p01
BEGIN DESCRIPTION:
----------MODEL BY WOOD PLC 2021----------
Stream Name: Crooked Fork
Flood Zone: Enhanced Approximate
Pocahontas County, WV
HEC-RAS Version: RAS 6.1.0
Vertical Datum: NAVD88
Projection: NAD 1983 StatePlane West Virginia S FIPS 4702 (US Feet)
Terrain: 1-meter LIDAR (FEMA Region III 3DEP collected 2016-2018)
Land Use: 2019 NLCD
Hydrologic Method:
WV SIR2010-5033 regression equations
Model Notes:
KWSEL used at tie in, Crooked Fork is more dominant in facc and flow than Old Field Fork upstream of their confluence
END DESCRIPTION:
DSS Export Rating Curves= 0
DSS Export Rating Curve Sorted= 0
DSS Export Volume Flow Curves= 0
DXF OffsetX= 0
DXF OffsetY= 0
DXF ScaleX= 0
DXF ScaleY= 0

--- CRKDFK.p01 (plan) ---

Plan Title=Floodplain
Program Version=6.10
Short Identifier=Floodplain
Geom File=g01
Flow File=f01
Subcritical Flow
K Sum by GR= 0
Std Step Tol= 0.01
Critical Tol= 0.01
Num of Std Step Trials= 20
Max Error Tol= 0.3
Flow Tol Ratio= 0.001
Split Flow NTrial= 30
Split Flow Tol= 0.02
Split Flow Ratio= 0.02
Log Output Level= 0
Friction Slope Method= 1
Unsteady Friction Slope Method= 2
Unsteady Bridges Friction Slope Method= 1
Parabolic Critical Depth
Global Vel Dist= 0 , 0 , 0
Global Log Level= 0
CheckData=True
Encroach Param=-1 ,0,0, 0
Mapping Interval=1HOUR
Computation Time Step Use Courant=        0
Computation Time Step Use Time Series=    0
Computation Time Step Count To Double=0
Computation Time Step Max Doubling=0
Computation Time Step Max Halving=0
Computation Time Step Residence Courant=0
Run HTab= 0
Run UNet= 0
Run Sediment= 0
Run PostProcess= 0
Run WQNet= 0
Run RASMapper=-1
UNET Theta= 0
UNET Theta Warmup= 0
UNET ZTol= 0
UNET ZSATol= 0
UNET MxIter= 0
UNET Max Iter WO Improvement= 0
UNET MaxInSteps= 0
UNET DtIC= 0
UNET DtMin= 0
UNET MaxCRTS= 0
UNET WFStab= 0
UNET SFStab= 0
UNET WFX= 1
UNET SFX= 1
UNET Gravity=32.174
UNET 1D Methodology=Finite Difference
UNET DSS MLevel= 1
UNET Pardiso=0
UNET DZMax Abort= 0
UNET Use Existing IB Tables= 0
UNET Froude Reduction=False
UNET Froude Limit= 0
UNET Froude Power= 0
UNET D1 Cores= 0
UNET WindReference=Eulerian
UNET WindDragFormulation=Hsu (1988)
UNET D2 Coriolis=0
UNET D2 Cores= 0
UNET D2 Theta= 1
UNET D2 Theta Warmup= 1
UNET D2 Z Tol= 0.01
UNET D2 Volume Tol= 0.01
UNET D2 Max Iterations= 20
UNET D2 Equation= 0
UNET D2 RampUpFraction=0.1
UNET D2 TimeSlices= 1
UNET D2 Turbulence Formulation=Non-Conservative (original)
UNET D2 Eddy Viscosity=0.3
UNET D2 Transverse Eddy Viscosity=0.1
UNET D2 Smagorinsky Mixing=0
UNET D2 BCVolumeCheck=0
UNET D2 Cores=0
UNET D2 SolverType=PARDISO (Direct)
UNET D2 Minimum Iterations= 2147483647
UNET D2 Maximum Iterations= 2147483647
UNET D2 Restart Number= 10
UNET D2 Relaxation Coeff=1.3
UNET D2 SOR Precondition Iterations= 10
UNET D2 ILUT Maximum Fill= 8
UNET D2 ILUT Tolerance=1E-08
UNET D1D2 MaxIter= 0
UNET D1D2 ZTol=0.01
UNET D1D2 QTol=0.1
UNET D1D2 MinQTol=1
Write IC File= 0
Write IC File at Fixed DateTime=0
Write IC File at Sim End=0
Echo Input=False
Echo Parameters=False
Echo Output=False
Write Detailed= 0
HDF Write Warmup=0
HDF Write Time Slices=0
HDF Flush=0
HDF Compression= 1
HDF Chunk Size= 1
HDF Spatial Parts= 1
HDF Use Max Rows=0
HDF Fixed Rows= 1
Calibration Method= 0
Calibration Iterations= 20
Calibration Max Change=0.05
Calibration Tolerance=0.2
Calibration Maximum=1.5
Calibration Minimum=0.5
Calibration Optimization Method= 1
WQ AD Non Conservative
WQ ULTIMATE=-1
WQ Max Comp Step=1HOUR
WQ Output Interval=15MIN
WQ Output Selected Increments= 0
WQ Output face flow=0
WQ Output face velocity=0
WQ Output face area=0
WQ Output face dispersion=0
WQ Output cell volume=0
WQ Output cell surface area=0
WQ Output cell continuity=0
WQ Output cumulative cell continuity=0
WQ Output face conc=0
WQ Output face dconc_dx=0
WQ Output face courant=0
WQ Output face peclet=0
WQ Output face adv mass=0
WQ Output face disp mass=0
WQ Output cell mass=0
WQ Output cell source sink temp=0
WQ Output nsm pathways=0
WQ Output nsm derived pathways=0
WQ Create Restart=0
WQ Fixed Restart=0
WQ System Summary=0
WQ Write To DSS=0
Sorting and Armoring Iterations= 10
XS Update Threshold= 0.02
Bed Roughness Predictor= 0
Hydraulics Update Threshold= 0.02
Energy Slope Method= 1
Volume Change Method= 1
Sediment Retention Method= 0
Sediment TS Multiplier= 1
Warm Up Method= 0
XS Weighting Method= 0
Number of US Weighted Cross Sections= 1
Number of DS Weighted Cross Sections= 1
Upstream XS Weight=0
Main XS Weight=1
Downstream XS Weight=0
Number of DS XS's Weighted with US Boundary= 1
Upstream Boundary Weight= 1
Weight of XSs Associated with US Boundary= 0
Number of US XS's Weighted with DS Boundary= 1
Downstream Boundary Weight= 0.5
Weight of XSs Associated with DS Boundary= 0.5
Percentile Method= 0
Sediment Output Level= 3
Mass or Volume Output= 0
Output Increment Type= 1
Profile and TS Output Increment= 1
Transport Output Increment 1
XS Output Flag= 0
XS Output Increment= 10
Read HDF5 Sediment Hotstart= 0
Sediment Hotstart Type= 0
Write Gradation File= 0
Read Gradation Hotstart= 0
Write HDF5 File= 1
Write Binary Output= 1
Write DSS Sediment File= 0
DSS Sediment Output Type= 1
SV Curve= 0
Specific Gage Flag= 0
Subcell Erosion Methods= 0
Subcell Deposition Methods= 0
Advection Scheme= 1
Matrix Solver= 0
Implicit Weighting Factor= 1
Maximum Outer Loop Convergence Iterations= 5
Convergence Maximum Absolute= 0.001
Convergence RMSE= 0.0001
Grain Fractions Max Abs Error= 0.001
Max Subgrid Regions= 1
Max Subgrid Length Scale= 3.402823E+38
Initial Layer Thickness= 3.402823E+38
Min Layer Thickness= 3.402823E+38
Max Layer Thickness= 3.402823E+38
Number of Layers= 5

--- CRKDFK.f01 (steady flow) ---

Flow Title=Flow
Program Version=6.10
Number of Profiles= 6
Profile Names=01pct,10pct,04pct,02pct,0_2pct,01plus
River Rch & RM=CRKDFK,Main            ,10897
     671     357     473     569     934     992
River Rch & RM=CRKDFK,Main            ,8991
     777     415     549     659    1080    1150
River Rch & RM=CRKDFK,Main            ,7792
     887     477     629     754    1230    1310
River Rch & RM=CRKDFK,Main            ,6471
     987     533     701     840    1370    1460
River Rch & RM=CRKDFK,Main            ,1703
    1120     605     794     950    1540    1650
River Rch & RM=CRKDFK,Main            ,0
    2030    1100    1430    1720    2860    2930
Boundary for River Rch & Prof#=CRKDFK,Main            , 1
Up Type= 0
Dn Type= 1
Dn Known WS=3049.3
Boundary for River Rch & Prof#=CRKDFK,Main            , 2
Up Type= 0
Dn Type= 1
Dn Known WS=3048
Boundary for River Rch & Prof#=CRKDFK,Main            , 3
Up Type= 0
Dn Type= 1
Dn Known WS=3048.4
Boundary for River Rch & Prof#=CRKDFK,Main            , 4
Up Type= 0
Dn Type= 1
Dn Known WS=3048.9
Boundary for River Rch & Prof#=CRKDFK,Main            , 5
Up Type= 0
Dn Type= 1
Dn Known WS=3050.7
Boundary for River Rch & Prof#=CRKDFK,Main            , 6
Up Type= 0
Dn Type= 1
Dn Known WS=3050.9
DSS Import GetInterval= 0
DSS Import GetPeak= 0
DSS Import FillOption= 0

--- CRKDFK.g01 (geometry) ---

Geom Title=Geometry
Program Version=6.10

River Reach=CRKDFK          ,Main
Reach XY= 30
2219042.77704822486320.304980561 2219379.6979623486173.868921727
 2219570.0401013486418.6171198932219761.61714597486459.590135068
2219909.19001356486643.5769718142220270.16895039486631.271878317
2220861.74388272486884.6378413892221404.10303421486554.411139637
2221580.55707763486345.7799952332221928.32114589486139.883097306
2222212.61093163485865.3019535542222364.79993172485825.820077151
2222409.35200797485668.128135309 2222731.4018888485379.789145067
2223153.96502006 485181.824974062223257.34998389485042.618887648
2223518.29500005485062.7080863122223645.31311873 485163.80696547
2224595.03005131485097.2729778142224881.51897964 484995.00710623
2224939.57004464484787.8461032212225183.50295572484793.000948563
2225606.63399921484591.8589623872225956.05685681484524.891904727
2225911.97098698484195.1100839822226084.76788548484013.927047387
2226143.75005098483639.3510248962226364.95498914483444.454104975
2226998.17911638483666.770917565 2227178.4166168 484173.32305406

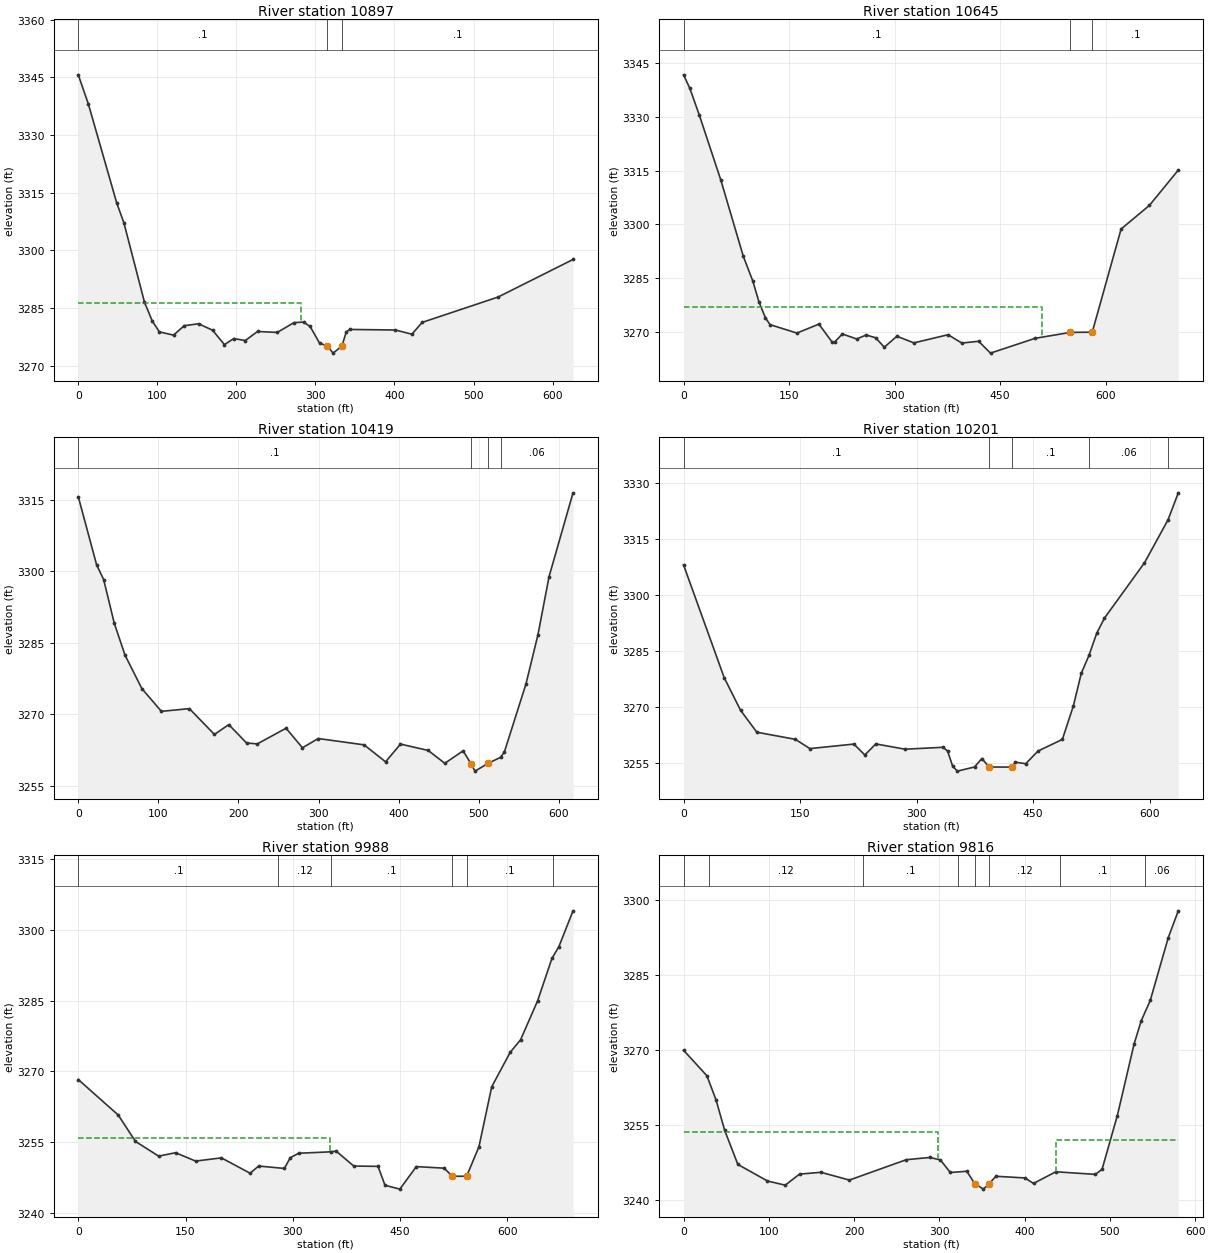
Type RM Length L Ch R = 1 ,10897   ,251.4,251.4,251.4
XS GIS Cut Line= 4
2218983.03192183 486616.63284336  2219077.795037486430.226598186
2218997.62435462486145.4130150142218921.54158634486051.426646124
#Sta/Elev= 30
       0 3345.66    12.8 3338.04    48.7 3312.29    57.7 3307.17    83.7 3286.55
    93.6 3281.61   102.6  3278.8   120.5 3277.95     134  3280.4   152.2 3280.91
   169.9 3279.23   184.9 3275.48   196.7 3277.06   211.3 3276.55   226.8  3278.9
   251.8 3278.66   272.9 3281.21     285 3281.34   293.3 3280.21   305.3 3275.86
     315 3275.14   322.4 3273.27  333.47  3275.1     339 3278.73   343.2 3279.43
   401.3 3279.28   422.1 3278.19     435 3281.26     531 3287.85   625.9 3297.63
#Mann= 3 ,-1,0
       0      .1       0     315    .045       0  333.47      .1       0
#XS Ineff= 2 , 0
          281.97 3286.18
Permanent Ineff=
       F       F
Bank Sta=315,333.47
XS Rating Curve= 0 ,0
Exp/Cntr=0.3,0.1

Type RM Length L Ch R = 1 ,10645   ,210.7,226.4,245.2
XS GIS Cut Line= 5
2219132.93119526 486697.053583012219311.21470202486342.800610427
2219276.86950975486241.2165156562219244.73098837 486155.51379198
2219232.37001861486048.385387384
#Sta/Elev= 30
       0 3341.74     8.8 3338.03    22.2 3330.62      53 3312.36    84.9 3291.12
    98.4 3284.21   107.3  3278.3   116.3 3273.96   122.9 3272.03   161.1 3269.68
   192.4 3272.17   210.8 3267.26   214.8 3267.18   225.7 3269.43   246.1 3268.03
   259.6 3269.14     273 3268.37   285.3 3265.73   303.2 3268.79   327.5 3266.94
     376 3269.22   395.5 3266.89   419.4 3267.39   436.3 3264.08   499.6 3268.21
   549.6 3269.86   580.9 3269.93   621.9 3298.71   662.1  3305.3   703.2 3315.16
#Mann= 3 ,-1,0
       0      .1       0   549.6    .045       0   580.9      .1       0
#XS Ineff= 2 , 0
             509 3276.97
Permanent Ineff=
       F       F
Bank Sta=549.6,580.9
XS Rating Curve= 0 ,0
Exp/Cntr(USF)=0,0
Exp/Cntr=0.3,0.1

Type RM Length L Ch R = 1 ,10419   ,220.8,218.3,218.5
XS GIS Cut Line= 3
2219205.95809048486697.4072557272219390.59043155486326.095174681
2219494.16955366486151.539799117
#Sta/Elev= 30
       0  3315.6    22.9  3301.3    31.7 3298.22    44.9 3289.07    58.3 3282.39
    79.4 3275.34   103.8 3270.57   138.7 3271.14     170 3265.72   187.9 3267.79
   210.2 3263.92   223.6 3263.75   259.4 3267.03   279.9 3262.93   299.6 3264.87
   356.9 3263.54   383.7 3259.98   402.3  3263.7   436.9 3262.37   457.6 3259.67
   480.5 3262.29   490.2  3259.6   495.3 3258.03   511.8 3259.67   527.2 3260.92
     532 3262.05   558.9 3276.28   573.9 3286.62   587.8 3298.85   617.7 3316.41
#Mann= 4 ,-1,0
       0      .1       0   490.2    .045       0   511.8      .1       0
   527.2     .06       0
Bank Sta=490.2,511.8
XS Rating Curve= 0 ,0
Exp/Cntr(USF)=0,0
Exp/Cntr=0.3,0.1

Type RM Length L Ch R = 1 ,10201   ,209.6,213,208.7
XS GIS Cut Line= 3
2219354.45692073 486767.464028262219623.88876392 486333.00746702
2219674.62744261486218.280124752
#Sta/Elev= 30
       0 3308.01    52.3 3277.79    73.3 3269.07    94.3 3263.17   143.9 3261.26
   162.6 3258.78   219.2 3259.99   233.3 3257.07   247.4 3260.03   285.1 3258.62
   334.1 3259.13   339.9 3258.08   346.3 3254.07   352.4 3252.74   374.5 3253.86
   383.9 3256.11   393.3 3253.84  422.47 3253.83   427.1 3255.13   440.4 3254.73
   456.1 3258.11   487.5 3261.24   501.6 3270.17   511.9 3278.98   521.8 3283.78
   531.7 3289.68   541.6 3293.72   593.2 3308.58   623.5 3320.09   636.7 3327.32
#Mann= 5 ,-1,0
       0      .1       0   393.3    .045       0  422.47      .1       0
   521.8     .06       0   623.5      .1       0
Bank Sta=393.3,422.47
XS Rating Curve= 0 ,0
Exp/Cntr=0.3,0.1

Type RM Length L Ch R = 1 ,9988    ,165.2,171.7,167.2
XS GIS Cut Line= 3
2219616.19180955486964.9473756452219637.40277767486652.364687468
2219852.86155917486340.898366035
#Sta/Elev= 30
       0 3268.27    55.9 3260.76      80 3255.17   112.4 3252.06   136.1 3252.78
   164.1 3251.01   200.2 3251.69   240.3 3248.44   252.3 3249.96   288.4 3249.45
   296.4 3251.72   308.5 3252.67   353.3 3252.97   360.7 3253.12   385.3 3249.96
   419.3 3249.89     429 3245.89   449.8 3245.07   472.8 3249.84   511.7 3249.51
  523.21  3247.8   543.2  3247.8   560.4 3254.04   578.3 3266.75   604.1 3274.03
   618.7 3276.72   642.5 3284.95   662.5 3293.93   672.2  3296.4     692    3304
#Mann= 6 ,-1,0
       0      .1       0     280     .12       0   353.3      .1       0
  523.21    .045       0   543.2      .1       0   663.3     .06       0
#XS Ineff= 2 , 0
          351.93 3255.87
Permanent Ineff=
       F       F
Bank Sta=523.21,543.2
XS Rating Curve= 0 ,0
Exp/Cntr(USF)=0,0
Exp/Cntr=0.3,0.1

Type RM Length L Ch R = 1 ,9816    ,155.8,148.7,141.3
XS GIS Cut Line= 4
2219727.13112905486923.4429890922219805.56936554486662.590596246
2219890.05840492 486539.516011322219935.53902323 486387.58221065
#Sta/Elev= 30
       0 3269.89    27.4 3264.78      38 3260.01    48.3 3253.84    63.7 3247.05
    98.4 3243.74   119.3  3242.9     136 3245.11   161.1 3245.48   194.5 3243.92
   261.3    3248   288.7 3248.44   301.2 3247.96   312.9 3245.44   332.3 3245.68
   341.4 3243.23   351.7 3242.11   358.7 3243.23   366.3 3244.68   400.3 3244.35
   410.5 3243.25   436.6 3245.58   483.1 3245.06   490.9 3246.08   508.8 3256.82
   528.5 3271.17   536.8 3275.77   547.4 3279.84   568.5 3292.39   580.3 3297.77
#Mann= 8 ,-1,0
       0      .1       0      30     .12       0     210      .1       0
  322.39     .12       0   341.4    .045       0   358.7     .12       0
  441.67      .1       0  541.67     .06       0
#XS Ineff= 2 , 0
          298.82 3253.57  436.73         3251.91
Permanent Ineff=
       F       F
Bank Sta=341.4,358.7
XS Rating Curve= 0 ,0
Exp/Cntr=0.3,0.1

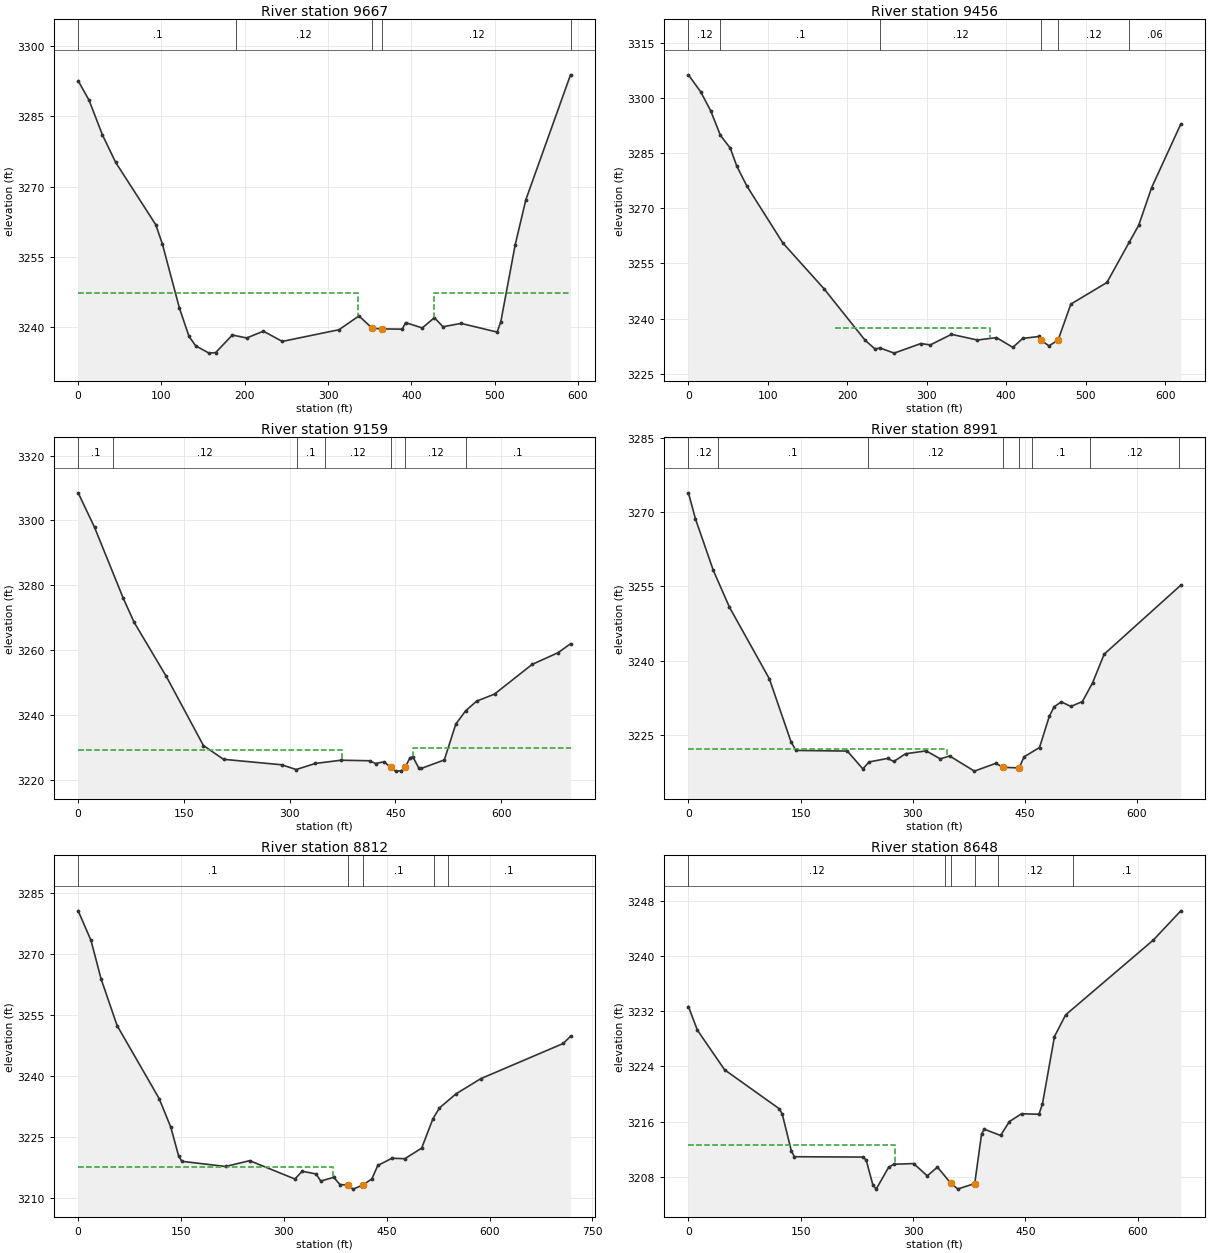
Type RM Length L Ch R = 1 ,9667    ,206.4,211.6,216.6
XS GIS Cut Line= 3
 2219984.5928349487006.2529451542219981.24373467486579.800849141
2220044.87663904486427.974972027
#Sta/Elev= 30
       0 3292.55    13.1  3288.4    29.1 3281.03    45.1 3275.13    93.1 3261.88
   101.1 3257.76   121.6 3244.07   133.1 3238.04   141.1 3236.04   157.1 3234.48
   165.1  3234.6   185.1 3238.34   202.3 3237.71   222.4 3239.16   245.1 3236.98
   313.1 3239.47   337.1 3242.41   353.1 3239.78   365.1 3239.65   389.1 3239.59
   393.1 3240.99   413.1 3239.85   427.7 3242.04     438  3240.1   459.7 3240.82
     503 3238.97   507.4 3241.15   524.7  3257.6   537.5  3267.2   591.1 3293.82
#Mann= 5 ,-1,0
       0      .1       0     190     .12       0   353.1    .045       0
   365.1     .12       0  591.09     .06       0
#XS Ineff= 2 , 0
          335.72 3247.32  427.07          3247.2
Permanent Ineff=
       F       F
Bank Sta=353.1,365.1
XS Rating Curve= 0 ,0
Exp/Cntr(USF)=0,0
Exp/Cntr=0.3,0.1

Type RM Length L Ch R = 1 ,9456    ,297.2,297.2,294.8
XS GIS Cut Line= 3
2220062.78539287487056.1236081692220185.13459365486590.499115458
2220183.43325615486452.101938729
#Sta/Elev= 30
       0 3306.28    15.5 3301.63    27.9 3296.55    40.3  3289.8    52.7 3286.35
    60.9 3281.44    73.4  3276.1   118.8 3260.57   170.5 3248.15   222.2 3234.16
   234.6 3231.78   241.6 3231.98     259 3230.61   292.5 3233.21   304.5 3232.85
   331.1 3235.72   363.8 3234.17   387.7 3234.83   408.4 3232.18   420.8 3234.61
   441.4 3235.14  444.373234.071   453.8 3232.58   465.3 3234.15   481.4 3243.94
   526.8 3249.82   554.7  3260.7   566.8 3265.36     583 3275.57   619.8 3292.91
#Mann= 6 ,-1,0
       0     .12       0    40.3      .1       0   241.6     .12       0
  444.37    .045       0   465.3     .12       0   554.7     .06       0
#XS Ineff= 1 ,-1
  184.86     380 3237.45
Permanent Ineff=
       F
Bank Sta=444.37,465.3
XS Rating Curve= 0 ,0
Exp/Cntr=0.3,0.1

Type RM Length L Ch R = 1 ,9159    ,165.8,167.4,168.3
XS GIS Cut Line= 3
2220366.52319004487163.9574730122220466.79390482 486622.04495831
2220519.74585532486484.595214456
#Sta/Elev= 30
       0 3308.53    23.2  3297.9    63.8 3276.07    79.3 3268.59   124.9 3251.89
   177.7  3230.5   206.2 3226.25   288.7 3224.56   309.3 3223.09   336.4 3224.97
     373 3225.97   413.7  3225.8   421.8 3224.95     434 3225.48   443.2 3223.76
   450.3  3222.6   458.4  3222.7   463.8 3223.79   470.6 3226.67   474.7 3227.05
   482.8 3223.72   486.9 3223.45   519.4 3226.06   535.7 3237.14   549.6 3241.22
   565.2  3244.2   590.6 3246.39     644 3255.56   680.6 3259.15   698.4 3261.92
#Mann= 7 ,-1,0
       0      .1       0      50     .12       0     310      .1       0
     350     .12       0   443.2    .045       0   463.8     .12       0
     550      .1       0
#XS Ineff= 2 , 0
          374.51 3229.25  475.15         3229.61
Permanent Ineff=
       F       F
Bank Sta=443.2,463.8
XS Rating Curve= 0 ,0
Exp/Cntr(USF)=0,0
Exp/Cntr=0.3,0.1

Type RM Length L Ch R = 1 ,8991    ,175.3,179.2,184.2
XS GIS Cut Line= 3
2220500.29713749487150.183274664 2220631.2743234486671.129731672
2220572.06545854486520.416257473
#Sta/Elev= 30
       0 3273.95     9.3 3268.72    33.3 3258.24    54.9 3250.79   108.2 3236.32
   137.5 3223.44     144 3221.81   212.5 3221.68   233.3 3218.08   241.7 3219.48
   266.4 3220.19   274.7 3219.58   290.5 3221.14     318 3221.72   336.9  3220.1
   349.4 3220.69   382.5 3217.62     411 3219.19     4213218.402   442.33218.262
   448.9 3220.51   469.6  3222.4   482.7 3228.71   489.2 3230.65   498.7 3231.64
   511.6 3230.71     527 3231.71   540.6  3235.5   556.1 3241.29   658.6 3255.26
#Mann= 8 ,-1,0
       0     .12       0      40      .1       0     240     .12       0
     421    .045       0   442.3     .12       0     460      .1       0
  536.64     .12       0  656.64      .1       0
#XS Ineff= 2 , 0
           346.5 3222.05
Permanent Ineff=
       F       F
Bank Sta=421,442.3
XS Rating Curve= 0 ,0
Exp/Cntr(USF)=0,0
Exp/Cntr=0.3,0.1

Type RM Length L Ch R = 1 ,8812    ,182,163.8,142
XS GIS Cut Line= 3
2220542.27860022487185.3635806612220817.17808792486744.848417982
2220830.69773486486546.560262915
#Sta/Elev= 30
       0  3280.5    18.7 3273.23    33.4 3263.78    56.8 3252.28   118.1 3234.33
   135.1 3227.29   146.4 3220.28   151.1  3218.9   215.1 3217.63   250.1 3219.06
   316.1 3214.55   326.7 3216.46     347 3215.79   353.8 3214.04   372.7 3214.97
   381.8 3213.18   393.4 3213.07     401 3212.06   415.1 3213.07   428.3 3214.56
     437 3217.89   457.6 3219.65   476.4 3219.54   500.9 3222.14   517.4 3229.38
   526.9 3232.03     551 3235.49   587.1 3239.22   707.4 3247.88     718 3249.65
#Mann= 5 ,-1,0
       0      .1       0   393.4    .045       0   415.1      .1       0
  519.25     .12       0  539.25      .1       0
#XS Ineff= 2 , 0
          371.34 3217.53
Permanent Ineff=
       F       F
Bank Sta=393.4,415.1
XS Rating Curve= 0 ,0
Exp/Cntr(USF)=0,0
Exp/Cntr=0.3,0.1

Type RM Length L Ch R = 1 ,8648    ,174.5,174.6,173.9
XS GIS Cut Line= 4
2220966.99556917487204.9662254942220992.67200427487034.162113741
2220884.38443015486830.9833664262220881.03532992486576.451748911
#Sta/Elev= 30
       0 3232.66    11.9 3229.25    48.3  3223.5   121.1 3217.88   125.2 3217.12
   137.3 3211.82   141.4 3210.92   232.8 3210.87   237.3 3210.46   246.4  3206.8
   250.7 3206.23   267.3 3209.39   274.3 3209.83   300.8 3209.93   318.9 3208.15
   332.5 3209.42   350.23207.106   359.7 3206.25   382.3 3207.04   391.4 3214.18
   394.9 3214.91   416.8    3214   428.6 3216.01   444.8 3217.14   468.1 3217.07
   472.8 3218.58   488.8 3228.32   503.7 3231.45   620.8 3242.28   657.5 3246.51
#Mann= 6 ,-1,0
       0     .12       0  342.72      .1       0   350.2    .045       0
   382.3      .1       0  412.96     .12       0  512.96      .1       0
#XS Ineff= 2 , 0
          276.06 3212.63
Permanent Ineff=
       F       F
Bank Sta=350.2,382.3
XS Rating Curve= 0 ,0
Exp/Cntr(USF)=0,0
Exp/Cntr=0.3,0.1

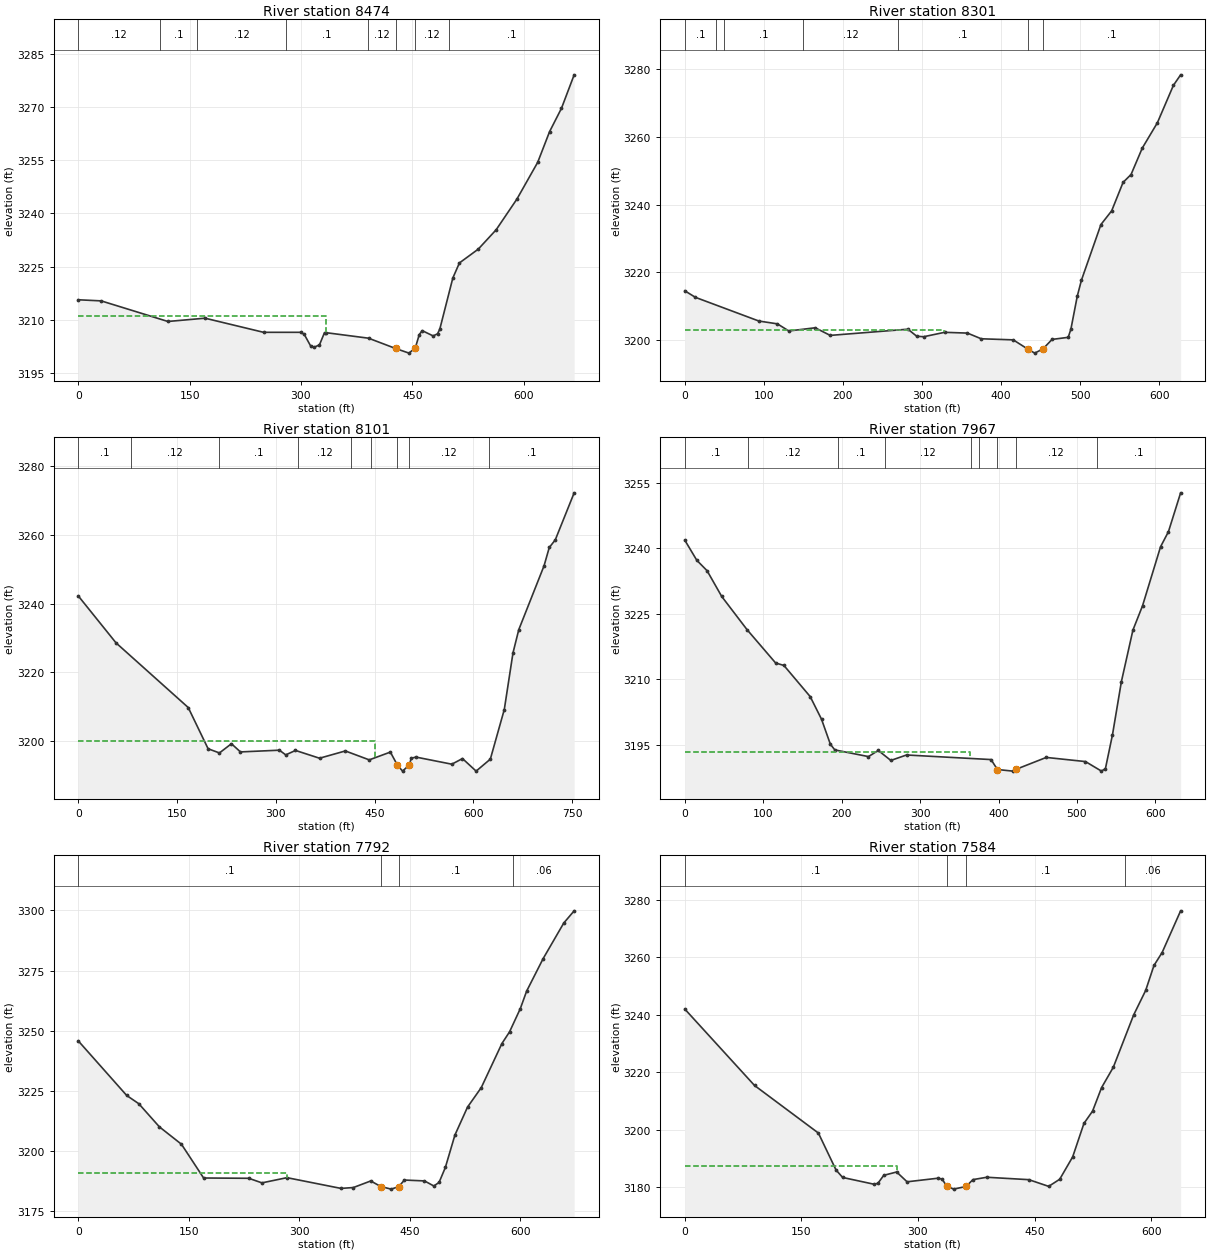
Type RM Length L Ch R = 1 ,8474    ,173.8,172.2,170.9
XS GIS Cut Line= 3
2221262.07745206487160.1962346822221012.08633126486703.162839928
2221006.08415611486556.095742813
#Sta/Elev= 30
       0  3215.6    30.8 3215.29   120.7 3209.47   170.7  3210.4   249.6 3206.41
   299.8 3206.41   304.4 3205.83   313.1 3202.52     318 3202.22   324.9 3202.86
   331.7 3206.31   333.7 3206.31     391 3204.75   427.5 3201.84   445.6 3200.53
   454.1 3202.02   459.4 3205.78   463.4 3206.88   478.1 3205.39     484 3205.99
     487 3207.27   504.6 3221.74   513.5 3226.01   538.9 3229.91     563 3235.38
     591 3244.06     619 3254.44     635 3263.11     651 3269.69   668.1 3279.15
#Mann= 8 ,-1,0
       0     .12       0     110      .1       0     160     .12       0
     280      .1       0     390     .12       0   427.5    .045       0
   454.1     .12       0     500      .1       0
#XS Ineff= 2 , 0
          333.63 3211.06
Permanent Ineff=
       F       F
Bank Sta=427.5,454.1
XS Rating Curve= 0 ,0
Exp/Cntr=0.3,0.1

Type RM Length L Ch R = 1 ,8301    ,198.7,200,200.9
XS GIS Cut Line= 2
2221431.49110308487047.9134171712221092.38578613486520.416257473
#Sta/Elev= 30
       0 3214.52    13.5 3212.58    93.6 3205.59   117.1 3204.75   131.6 3202.65
   164.9 3203.59   183.9 3201.34   282.2 3203.17   293.3  3201.1     302 3200.94
   328.6 3202.25   357.5 3202.02   374.9 3200.34   415.4 3200.02   433.8 3197.29
   442.6  3196.1     453 3197.35   464.5 3200.15   484.9 3200.77   488.3 3203.15
   496.4 3212.95   501.7  3217.7   526.3  3234.1   539.9 3238.16   554.3 3246.56
   564.4 3248.89   578.6  3256.7   597.7 3264.18     618 3275.25   627.1 3278.35
#Mann= 7 ,-1,0
       0      .1       0      40     .12       0      50      .1       0
     150     .12       0     270      .1       0   433.8    .045       0
     453      .1       0
#XS Ineff= 2 , 0
          328.15 3202.93
Permanent Ineff=
       F       F
Bank Sta=433.8,453
XS Rating Curve= 0 ,0
Exp/Cntr(USF)=0,0
Exp/Cntr=0.3,0.1

Type RM Length L Ch R = 1 ,8101    ,136.6,134.2,132.6
XS GIS Cut Line= 3
2221651.35019482486974.7859614372221519.98645573486860.422235638
2221243.34987575486351.967292555
#Sta/Elev= 30
       0  3242.2    57.3 3228.53   166.9  3209.7   197.1 3197.68   214.3 3196.47
   232.5 3199.15   246.2 3196.77   305.4 3197.27     315  3195.9   329.8  3197.2
   366.3 3194.93   405.5 3197.05   441.8 3194.45   473.9 3196.72   484.63192.896
   492.4 3191.19   502.3  3192.9   505.7 3194.91   512.6 3195.27   567.2 3193.19
   583.4 3194.83   604.1 3191.17   625.7 3194.66   646.9 3209.12   660.1 3225.62
   668.9 3232.39   707.3 3251.01   715.2 3256.33   724.3 3258.54     753 3272.26
#Mann= 9 ,-1,0
       0      .1       0      80     .12       0  214.17      .1       0
  334.17     .12       0  414.17      .1       0  444.17     .12       0
   484.6    .045       0   502.3     .12       0  624.17      .1       0
#XS Ineff= 2 , 0
           450.7 3199.85
Permanent Ineff=
       F       F
Bank Sta=484.6,502.3
XS Rating Curve= 0 ,0
Exp/Cntr(USF)=0,0
Exp/Cntr=0.3,0.1

Type RM Length L Ch R = 1 ,7967    ,178.9,175.5,174.8
XS GIS Cut Line= 3
2221761.84869053486780.7468629692221615.60464713486684.739323029
2221338.74569475486320.803764652
#Sta/Elev= 30
       0 3241.88    15.3 3237.27    28.4 3234.88    47.1 3228.97    79.4 3221.36
   115.8 3213.73   126.4 3213.16   159.9 3206.02   174.3 3200.85   185.6 3195.11
   191.3  3193.8   234.2 3192.27   246.7 3193.68   262.7 3191.39   282.7 3192.64
   390.5 3191.59   398.6 3189.31   418.4 3188.94   422.6 3189.37   460.9 3192.08
   510.9 3191.13   531.2 3188.95   536.3  3189.5   545.3 3197.26   556.7 3209.48
   571.4 3221.28   583.6 3226.82   606.6 3240.36   616.7 3243.84   632.2 3252.73
#Mann= 9 ,-1,0
       0      .1       0      80     .12       0  194.94      .1       0
  254.94     .12       0  364.94      .1       0  374.94     .12       0
   398.6    .045       0   422.6     .12       0  524.94      .1       0
#XS Ineff= 2 , 0
          363.74 3193.25
Permanent Ineff=
       F       F
Bank Sta=398.6,422.6
XS Rating Curve= 0 ,0
Exp/Cntr(USF)=0,0
Exp/Cntr=0.3,0.1

Type RM Length L Ch R = 1 ,7792    ,203.4,208.1,214.3
XS GIS Cut Line= 2
2221866.16854463486651.7857088412221394.80453965486171.148969331
#Sta/Elev= 30
       0 3245.78    65.7 3223.14    82.1 3219.72   110.1  3210.1     140  3202.9
   170.1 3188.88   231.4 3188.76   249.3 3186.86   283.3 3189.02   356.6 3184.56
   373.4 3184.92     397 3187.65   410.6 3185.35   424.7 3184.26     435 3185.28
   442.7 3188.03     470 3187.67   482.7 3185.56   489.8 3187.05   498.3 3193.24
   511.3 3206.71   528.4  3218.3   547.1 3226.42   575.1  3244.7   585.5 3249.57
   600.1  3259.2   608.7 3266.48   631.1 3279.97   659.1 3294.74   673.2  3299.8
#Mann= 4 ,-1,0
       0      .1       0   410.6    .045       0     435      .1       0
     590     .06       0
#XS Ineff= 2 , 0
          282.76 3190.82
Permanent Ineff=
       F       F
Bank Sta=410.6,435
XS Rating Curve= 0 ,0
Exp/Cntr(USF)=0,0
Exp/Cntr=0.3,0.1

Type RM Length L Ch R = 1 ,7584    ,228.3,223.7,219.1
XS GIS Cut Line= 4
2221984.00567248486483.7933092012221780.82692517486309.640097217
2221719.42675428 486185.723388692221541.92444206486036.130245062
#Sta/Elev= 30
       0 3241.97    89.7  3215.4   171.9 3198.84   194.6 3185.99   203.1 3183.39
   243.7 3181.02   248.5 3181.36     256 3184.13   272.6 3185.29     286 3181.88
   326.2 3183.14   331.1  3182.8   337.1 3180.35     346 3179.33   361.9 3180.26
   370.8 3182.64   388.6 3183.46   442.7 3182.62   468.2 3180.29   482.4 3182.76
   499.1 3190.55   513.6  3202.2   524.7 3206.47   536.3 3214.65   551.4 3221.74
   577.5 3239.89     593 3248.44   603.7 3257.14   614.2 3261.65     638 3276.15
#Mann= 4 ,-1,0
       0      .1       0   337.1    .045       0   361.9      .1       0
   565.9     .06       0
#XS Ineff= 2 , 0
           272.7 3187.22
Permanent Ineff=
       F       F
Bank Sta=337.1,361.9
XS Rating Curve= 0 ,0
Exp/Cntr(USF)=0,0
Exp/Cntr=0.3,0.1

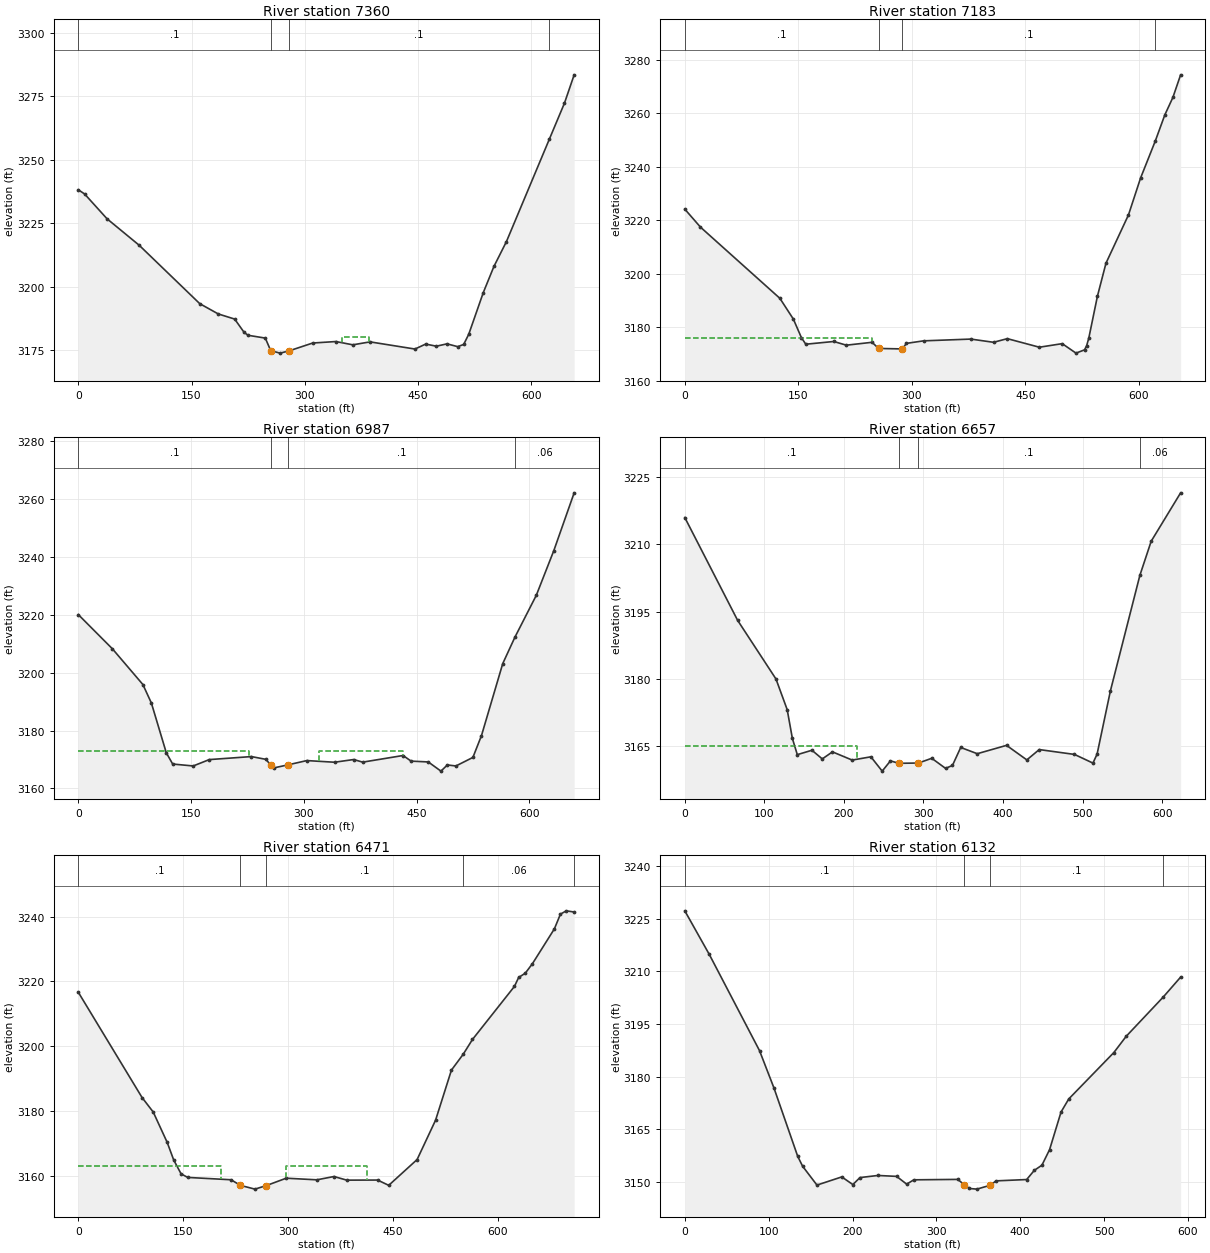
Type RM Length L Ch R = 1 ,7360    ,177,177,177.8
XS GIS Cut Line= 3
2222117.68342916486329.4929289572221804.35031447485976.421544321
2221673.18338056485845.890787703
#Sta/Elev= 30
       0 3238.13     8.3 3236.49    38.1  3226.7    80.6 3216.31   160.9  3193.3
   185.5 3189.24   207.2 3187.23   219.7 3181.99     225 3180.84   247.8 3179.74
  254.933174.804   267.4 3173.82   279.5 3174.73   310.6  3177.8   341.3 3178.38
   363.8 3177.09   386.6 3178.25   446.1 3175.43   460.3 3177.38   474.5 3176.55
   488.6 3177.47   502.8 3176.37   510.7 3177.24   517.4 3181.25   536.7 3197.68
   550.8 3207.97   567.4 3217.77   624.1 3257.98   644.2 3272.21   657.1  3283.4
#Mann= 4 ,-1,0
       0      .1       0  254.93    .045       0   279.5      .1       0
   624.1     .07       0
#XS Ineff= 1 ,-1
   349.8   385.5    3180
Permanent Ineff=
       F
Bank Sta=254.93,279.5
XS Rating Curve= 0 ,0
Exp/Cntr=0.3,0.1

Type RM Length L Ch R = 1 ,7183    ,196,195.8,195.4
XS GIS Cut Line= 2
2222241.88639023486204.7016233292221808.73609376485713.500256194
#Sta/Elev= 30
       0 3224.17    20.7 3217.44   125.6 3190.82   143.4 3183.06     154 3176.13
   159.8 3173.67   196.7 3174.69   213.4 3173.31   247.4 3174.39   255.9 3172.09
   287.3 3171.91   292.8 3173.99   315.4 3174.93   377.8 3175.59   407.8 3174.39
     426 3175.75   468.3 3172.55   498.5 3173.88   516.7 3170.34     528 3171.57
   530.8 3173.13   533.7 3176.07     545 3191.61   556.3 3203.96     586    3222
     602  3235.8   621.5 3249.68     634 3259.38   644.7 3265.94   654.9 3274.38
#Mann= 4 ,-1,0
       0      .1       0   255.9    .045       0   287.3      .1       0
   621.5     .06       0
#XS Ineff= 2 , 0
           247.4    3176
Permanent Ineff=
       F       F
Bank Sta=255.9,287.3
XS Rating Curve= 0 ,0
Exp/Cntr(USF)=0,0
Exp/Cntr=0.3,0.1

Type RM Length L Ch R = 1 ,6987    ,328.7,329.9,327.8
XS GIS Cut Line= 2
2222383.62238928486066.9832077272221943.58878313485575.624079767
#Sta/Elev= 30
       0 3219.99    45.4 3208.17    85.9 3195.86    97.2 3189.47     117 3172.33
   125.5 3168.44   152.8 3167.77   174.2 3169.97   230.3 3171.01   249.4 3170.06
   255.8 3168.18   260.2 3167.11   278.5 3168.13     304 3169.63   340.8 3169.06
   366.3 3169.99   378.3 3169.09     432 3171.38   442.7 3169.44   465.5 3169.16
   482.4 3165.99   490.9 3168.12   502.3 3167.77   524.9 3170.72   536.3 3178.24
   564.6 3203.09   580.8 3212.21   609.2 3226.63   632.6 3242.11   659.6 3262.01
#Mann= 4 ,-1,0
       0      .1       0   255.8    .045       0   278.5      .1       0
   580.8     .06       0
#XS Ineff= 2 ,-1
       0  227.68 3173.09     320   431.5 3173.09
Permanent Ineff=
       F       F
Bank Sta=255.8,278.5
XS Rating Curve= 0 ,0
Exp/Cntr=0.3,0.1

Type RM Length L Ch R = 1 ,6657    ,187.5,185.7,185.7
XS GIS Cut Line= 2
2222582.37824699485884.3043679482222184.95168631485404.266668248
#Sta/Elev= 30
       0 3215.95    66.4 3193.05   114.6 3179.99   128.7 3173.16   135.2 3166.76
   141.4 3163.14   159.8 3164.12   172.8 3162.19   185.6 3163.76   210.4 3161.93
   233.9 3162.66   248.1 3159.47   258.5 3161.76   268.9 3161.21   293.73161.275
   310.4 3162.33   327.7 3160.09   336.4 3160.73   346.8 3164.74   367.6 3163.35
   404.4 3165.21   429.9 3161.97   445.5 3164.27   489.8 3163.19     513 3161.26
   518.2 3163.25     535 3177.38     572 3203.08   586.2 3210.67   623.2 3221.45
#Mann= 4 ,-1,0
       0      .1       0   268.9    .045       0   293.7      .1       0
     572     .06       0
#XS Ineff= 2 , 0
           216.7    3165
Permanent Ineff=
       F       F
Bank Sta=268.9,293.7
XS Rating Curve= 0 ,0
Exp/Cntr(USF)=0,0
Exp/Cntr=0.3,0.1

Type RM Length L Ch R = 1 ,6471    ,337.6,339.4,342.3
XS GIS Cut Line= 2
2222717.71466511 485781.694119312222288.07796549485217.602769082
#Sta/Elev= 30
       0 3216.63    91.2 3184.14   107.1 3179.69   127.1 3170.31   136.4 3164.89
     147  3160.6   156.5 3159.51   218.4 3158.79   231.9 3157.05   252.6  3155.9
   268.8 3156.99   297.3 3159.27   341.1 3158.77   365.6 3159.79   383.9 3158.67
     428  3158.7   443.9 3157.07   484.5 3165.03   510.9 3177.17   533.6 3192.63
   550.5 3197.54   563.7 3202.09   623.7 3218.45   629.7  3221.2   639.2 3222.53
   649.4 3225.45   680.8  3236.2   689.5 3240.76   697.9 3241.77   709.1  3241.4
#Mann= 5 ,-1,0
       0      .1       0   231.9    .045       0   268.8      .1       0
   550.5     .06       0   709.1      .1       0
#XS Ineff= 2 ,-1
       0   204.1    3163   297.3     413    3163
Permanent Ineff=
       F       F
Bank Sta=231.9,268.8
XS Rating Curve= 0 ,0
Exp/Cntr(USF)=0,0
Exp/Cntr=0.3,0.1

Type RM Length L Ch R = 1 ,6132    ,298.1,297.2,297.6
XS GIS Cut Line= 3
2222918.62391314485656.512203232 2222808.8965546485367.511977225
2222672.89644825485120.239056577
#Sta/Elev= 30
       0 3227.27    29.2 3214.86    89.1 3187.46   106.3 3176.84   134.7 3157.33
   140.5 3154.54   157.6 3149.17   187.2  3151.5   200.4 3149.32   208.9 3151.31
   230.3 3151.91   252.6 3151.65   264.6 3149.44   273.1 3150.67   325.5 3150.79
   333.5 3149.24   339.2 3148.21   348.3 3148.02   364.4 3149.13   371.1 3150.37
   407.7 3150.75   416.8 3153.36   425.9 3154.84     435 3159.25   448.7 3169.98
   457.9  3173.7   511.7 3186.92   526.4 3191.54   570.6 3202.73   591.3 3208.39
#Mann= 4 ,-1,0
       0      .1       0   333.5    .045       0   364.4      .1       0
   570.6     .06       0
Bank Sta=333.5,364.4
XS Rating Curve= 0 ,0
Exp/Cntr(USF)=0,0
Exp/Cntr=0.3,0.1