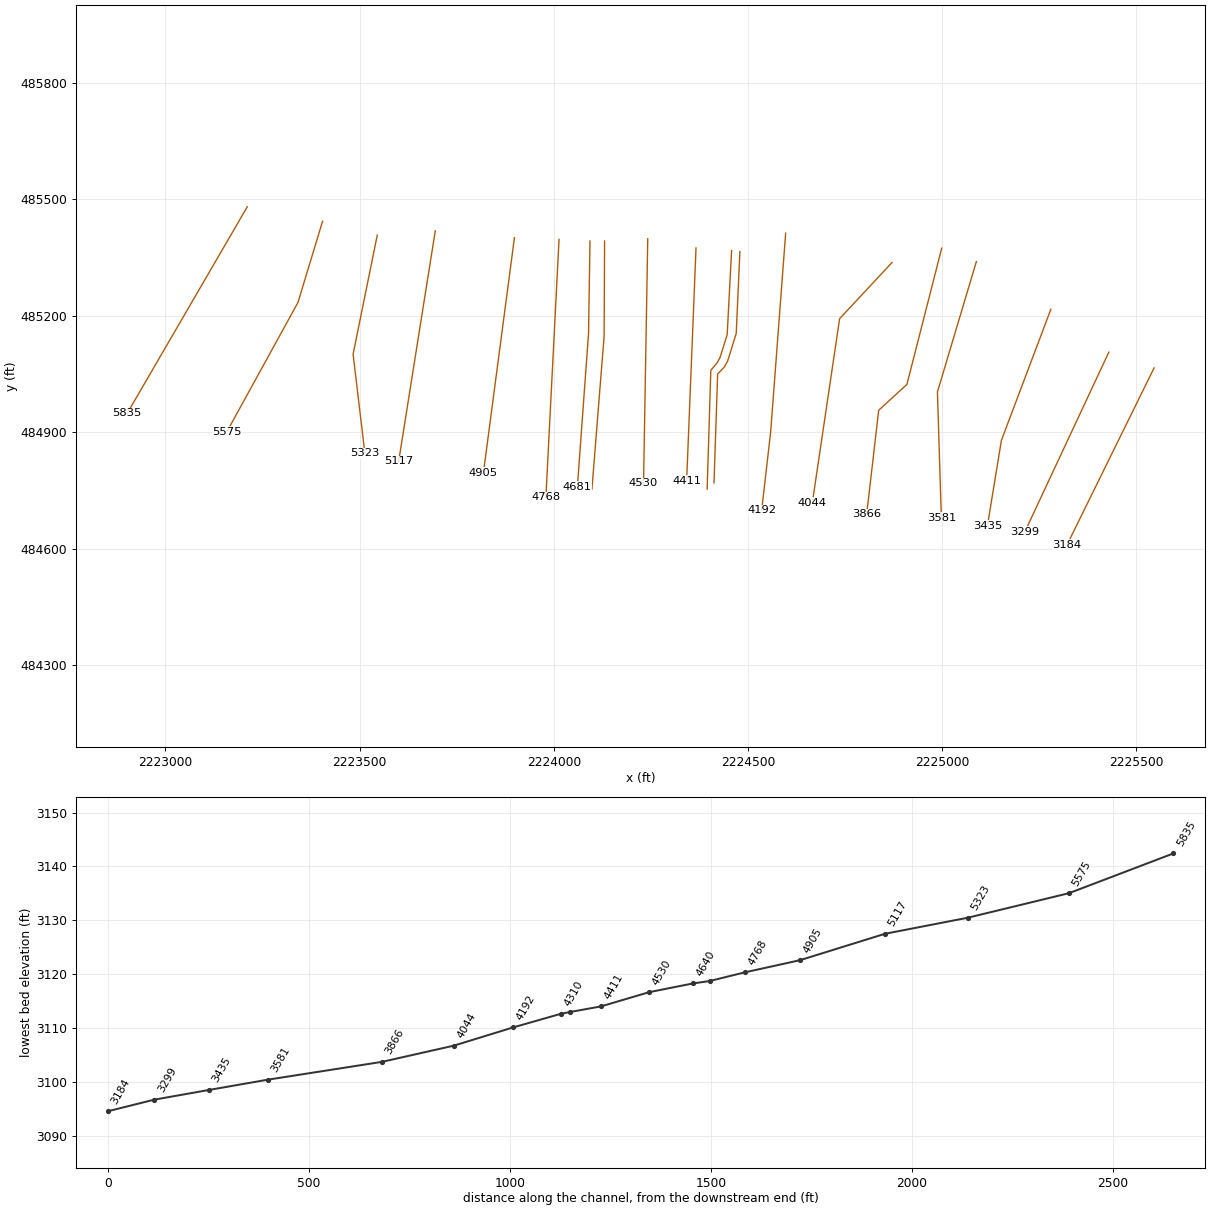
HEC-RAS study CRKDFK.prj: CRKDFK

--- CRKDFK.g01 (geometry) --- (continued)

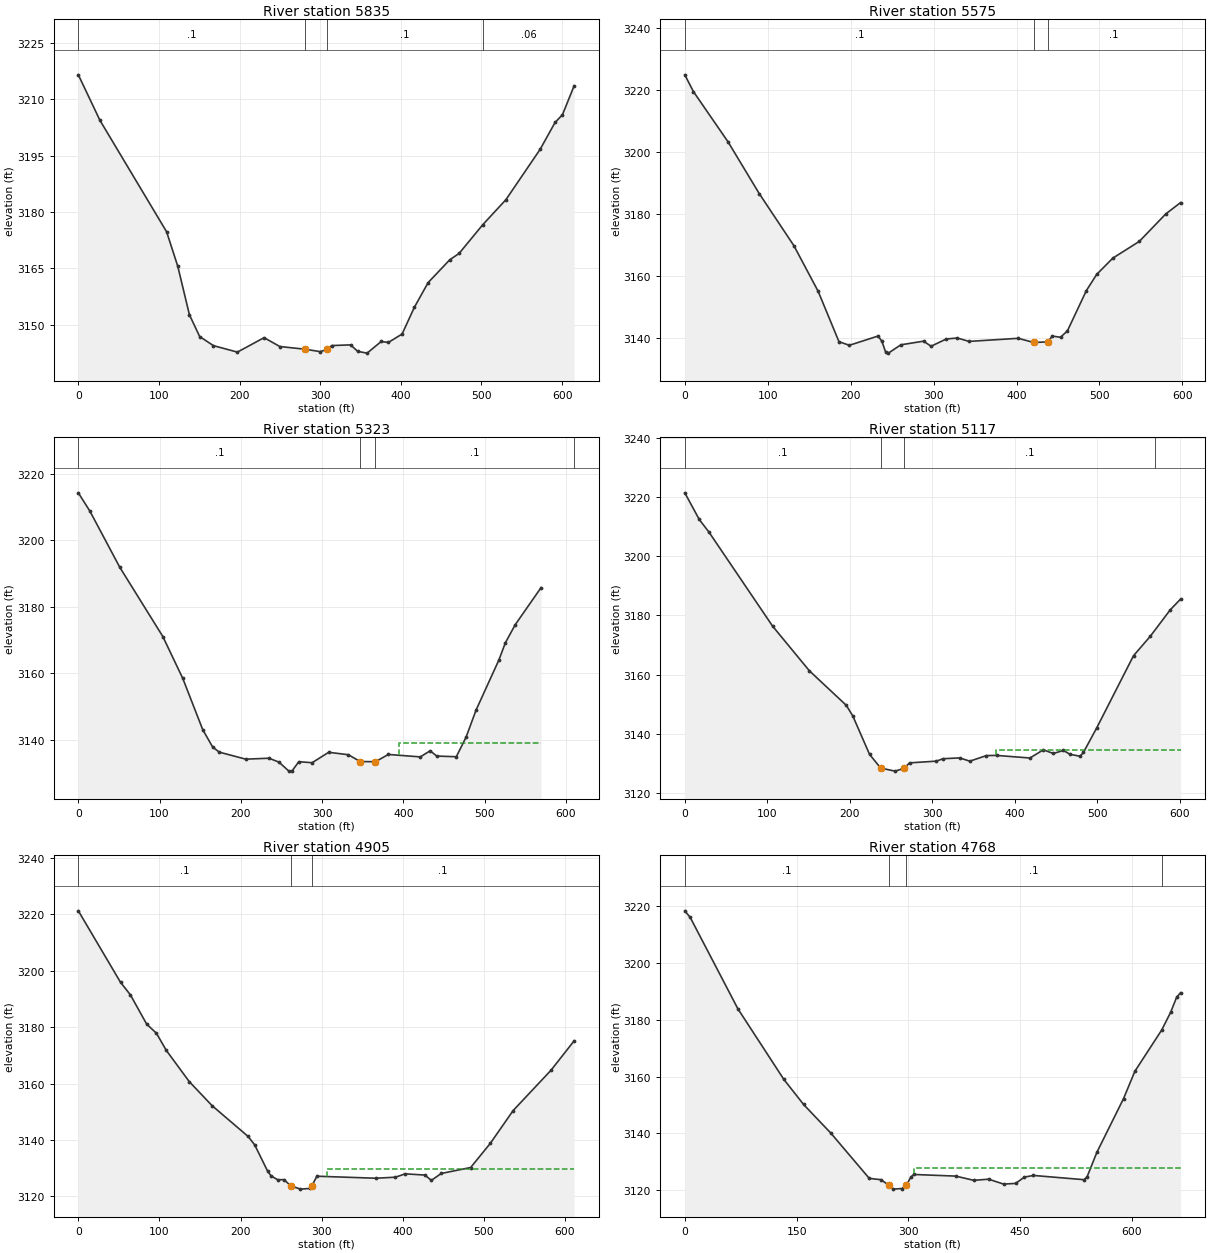
Type RM Length L Ch R = 1 ,5835    ,263.2,260,260.3
XS GIS Cut Line= 2
2223210.71505066 485480.330247272222901.62389985484948.693467877
#Sta/Elev= 30
       0 3216.53    26.8 3204.41   109.5 3174.73   123.3 3165.58   137.8 3152.63
   150.5 3146.84   167.5 3144.42   197.3 3142.69   230.4 3146.54   249.9 3144.18
   281.3 3143.46   300.1 3142.81     309 3143.47   314.3 3144.43   337.7 3144.62
   346.5 3142.89   358.2 3142.42   375.7 3145.52   384.5 3145.26   401.6 3147.51
   416.7 3154.59   433.9 3161.21   460.6 3167.26   472.3 3168.97   501.6 3176.61
   530.3 3183.27   572.8 3196.69   591.3 3203.84   600.5 3205.91     615 3213.63
#Mann= 4 ,-1,0
       0      .1       0   281.3    .045       0     309      .1       0
   501.6     .06       0
Bank Sta=281.3,309
XS Rating Curve= 0 ,0
Exp/Cntr(USF)=0,0
Exp/Cntr=0.3,0.1

Type RM Length L Ch R = 1 ,5575    ,246.1,251.9,262.6
XS GIS Cut Line= 3
2223404.55991053485443.0878495812223341.26191618  485234.1039952
 2223158.4010436484901.538342315
#Sta/Elev= 30
       0 3224.83    10.4 3219.42    52.1 3203.22    89.8 3186.49   131.6 3169.68
   160.8 3154.98   185.9 3138.73   198.4 3137.56   233.1 3140.55   237.7 3138.84
   242.2 3135.35   245.5 3135.03   260.5 3137.71   287.9 3138.89     297 3137.25
   315.3 3139.59   328.8 3139.91   342.7 3138.81     402 3139.81   420.8 3138.46
   437.8 3138.66   443.1 3140.53   453.1 3140.15   461.4 3142.22   484.2 3155.19
   496.7 3160.44   516.1 3165.67   548.1 3171.09     580 3179.95   597.9 3183.62
#Mann= 3 ,0,0
       0      .1       0   420.8    .045       0   437.8      .1       0
Bank Sta=420.8,437.8
XS Rating Curve= 0 ,0
Exp/Cntr(USF)=0,0
Exp/Cntr=0.3,0.1

Type RM Length L Ch R = 1 ,5323    ,217.3,205.9,202.4
XS GIS Cut Line= 3
  2223545.344824485407.1792959172223483.11856934485100.697894091
2223513.47921423484845.671662961
#Sta/Elev= 30
       0 3214.36    14.3 3208.81      51 3191.93   104.1 3171.01   128.6  3158.4
   153.1 3142.99   165.3 3137.76   173.5 3136.19   206.1 3134.08   234.7 3134.36
     247 3133.18   259.2 3130.47   263.3 3130.61   271.4 3133.31   287.8 3133.01
   308.2 3136.15   332.4 3135.41  346.95 3133.36   365.8  3133.3   381.6  3135.5
     421 3134.76   433.1  3136.6   441.2 3135.01   465.3 3134.81   477.4 3140.75
   489.6 3148.87   517.7 3163.96   525.7 3169.16   537.8  3174.6   569.6 3185.78
#Mann= 4 ,-1,0
       0      .1       0  346.95    .045       0   365.8      .1       0
  610.37     .06       0
#XS Ineff= 2 , 0
                          394.15         3138.99
Permanent Ineff=
       F       F
Bank Sta=346.95,365.8
XS Rating Curve= 0 ,0
Exp/Cntr(USF)=0,0
Exp/Cntr=0.3,0.1

Type RM Length L Ch R = 1 ,5117    ,211.5,211.7,212.4
XS GIS Cut Line= 2
2223694.74223372485418.2818532062223600.46943272484824.826843651
#Sta/Elev= 30
       0 3221.39    17.5 3212.41    29.5 3208.05   106.4 3176.41     151 3161.34
   195.7  3149.7   203.6 3146.11   223.9 3133.15   237.4 3128.52   254.8 3127.49
   265.3 3128.39   272.5 3130.28   304.9 3130.86     313 3131.68   333.2 3131.95
   345.4 3130.85   365.6 3132.74   377.8 3132.79   418.3 3131.92   434.5 3134.68
   446.6 3133.44   458.8 3134.47   466.9 3133.17     479  3132.5   483.1  3133.8
   499.3 3142.12   543.8 3166.43   564.1 3172.98   588.4 3181.94   600.9 3185.56
#Mann= 4 ,-1,0
       0      .1       0   237.4    .045       0   265.3      .1       0
     570     .06       0
#XS Ineff= 2 , 0
                          376.82         3134.73
Permanent Ineff=
       F       F
Bank Sta=237.4,265.3
XS Rating Curve= 0 ,0
Exp/Cntr(USF)=0,0
Exp/Cntr=0.3,0.1

Type RM Length L Ch R = 1 ,4905    ,136,137.4,138.8
XS GIS Cut Line= 2
2223898.57099751485400.6948867482223818.63902994484794.665241743
#Sta/Elev= 30
       0  3221.3      52 3195.95    64.1 3191.53    84.2 3181.14    96.3 3177.87
   108.4 3171.82   136.7 3160.74   164.9 3152.19   209.3 3141.27   217.4  3138.3
   233.5 3128.88   237.6  3127.3   245.6 3125.92   253.7 3125.93   261.8 3123.75
   273.9 3122.58     286 3122.84  288.05  3123.8   294.1 3127.16   366.7 3126.45
   390.9 3126.81     403    3128   427.2 3127.57   435.3  3125.7   447.4 3128.13
   483.7 3130.25   507.8 3138.77   536.1 3150.46   582.7 3164.73   611.3  3175.2
#Mann= 3 ,-1,0
       0      .1       0   261.8    .045       0  288.05      .1       0
#XS Ineff= 2 , 0
                           306.1         3129.61
Permanent Ineff=
       F       F
Bank Sta=261.8,288.05
XS Rating Curve= 0 ,0
Exp/Cntr(USF)=0,0
Exp/Cntr=0.3,0.1

Type RM Length L Ch R = 1 ,4768    ,87.7,87.4,87.1
BEGIN DESCRIPTION:
xs 4
END DESCRIPTION:
XS GIS Cut Line= 2
2224013.44605384485396.3544025262223979.54748013484731.894862235
#Sta/Elev= 30
       0 3218.38     7.2 3216.09    71.3 3183.83   132.8 3159.02   159.4 3150.15
   196.2 3139.98   247.5 3124.11   263.5 3123.63  273.56  3121.7   279.5 3120.32
   291.6 3120.54  297.16  3121.7   303.6 3124.65   307.6 3125.48   363.6 3124.91
   387.7 3123.42   407.7 3123.82   427.7  3122.1   443.8 3122.33   455.8 3124.57
   467.8 3125.14   535.9 3123.64   539.9 3124.73     553 3133.33   588.7 3152.22
     604 3161.88     640 3176.42     652 3182.68     660 3187.98   665.3 3189.54
#Mann= 4 ,-1,0
       0      .1       0  273.56    .045       0  297.16      .1       0
     640     .06       0
#XS Ineff= 2 , 0
                           307.6         3127.66
Permanent Ineff=
       F       F
Bank Sta=273.56,297.16
XS Rating Curve= 0 ,0
Exp/Cntr=0.5,0.3

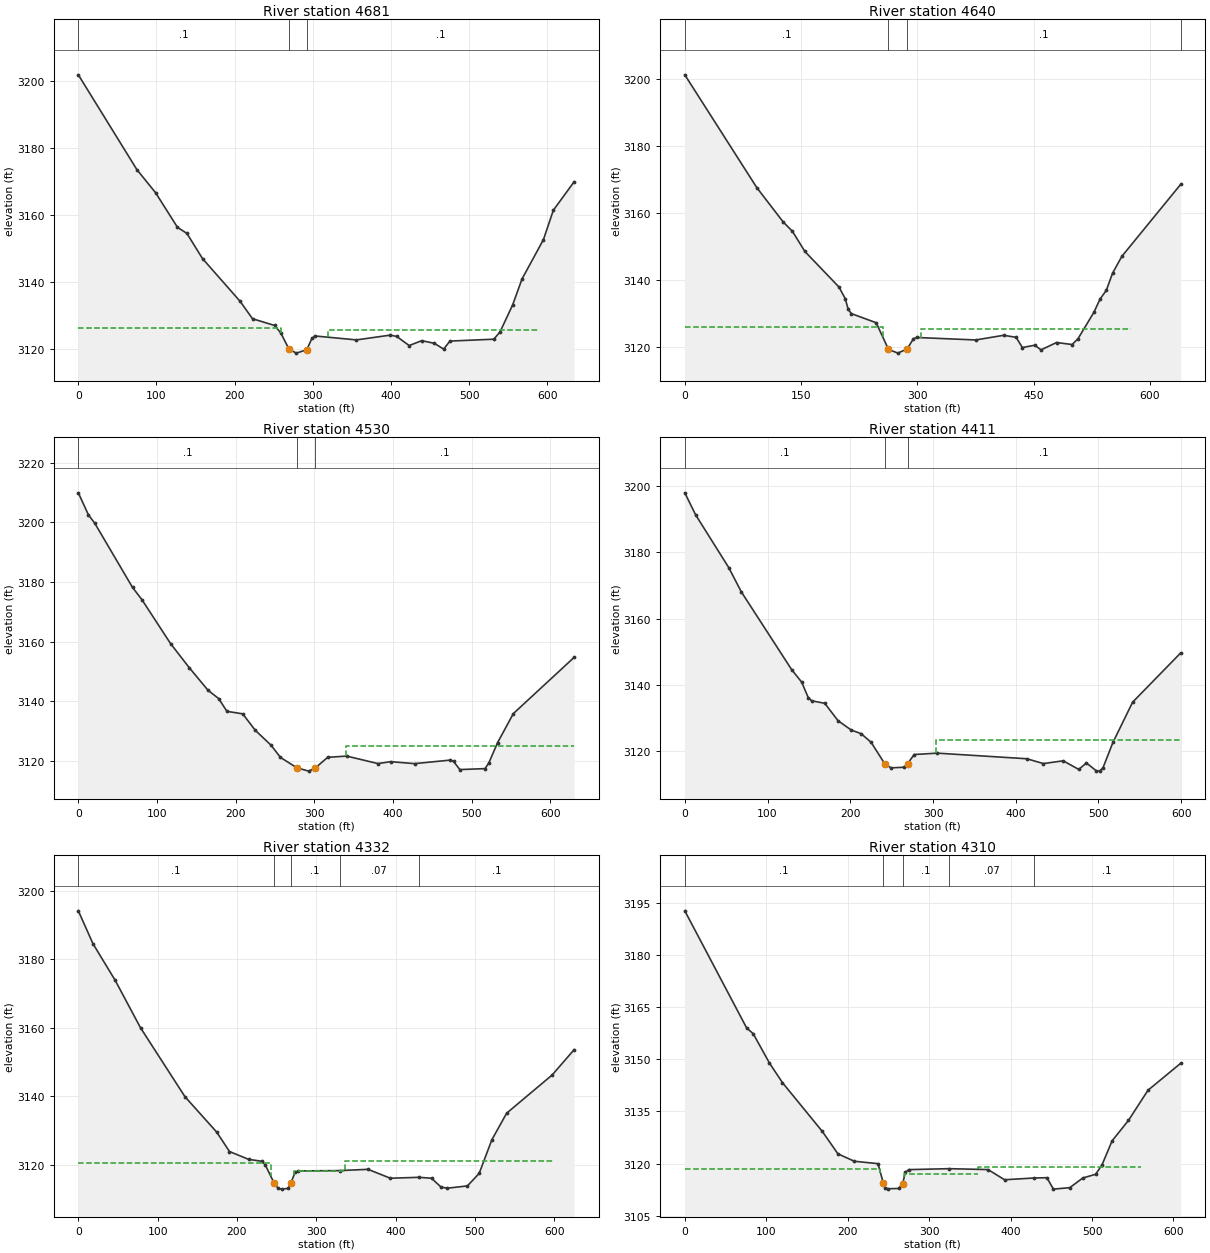
Type RM Length L Ch R = 1 ,4681    ,41.6,40.4,41
BEGIN DESCRIPTION:
xs 3
END DESCRIPTION:
XS GIS Cut Line= 3
2224093.16122661485392.0628791852224089.40576913485154.217238637
2224060.61392843 484758.64238383
#Sta/Elev= 30
       0 3201.83    74.9 3173.53    98.9 3166.61   126.9 3156.27   138.9 3154.48
   158.9 3146.95   206.9 3134.22   222.9 3128.98   251.2 3126.97     259 3124.75
   269.6  3119.9     279 3118.71   292.3 3119.73   299.1 3123.19   303.1 3123.83
   355.9 3122.66   399.3 3124.09   407.4 3123.69   423.4 3120.97   439.4 3122.43
   455.5 3121.65   467.5 3119.91   475.5 3122.31   531.7 3122.87   539.7 3125.08
   555.8 3133.12   567.8 3140.87   595.2 3152.62   607.9  3161.4   634.5  3169.9
#Mann= 3 ,0,0
       0      .1       0   269.6    .045       0   292.3      .1       0
#XS Ineff= 3 ,-1
       0   259.6  3126.3   302.3     320 3121.86     320  590.04 3125.75
Permanent Ineff=
       F       F       F
Bank Sta=269.6,292.3
XS Rating Curve= 0 ,0
Exp/Cntr(USF)=0,0
Exp/Cntr=0.5,0.3

Type RM Length L Ch R = 1 ,4640    ,109.1,110.2,111.2
BEGIN DESCRIPTION:
xs 2
END DESCRIPTION:
XS GIS Cut Line= 3
2224130.71580143485392.0628791852224129.46398227485146.706323672
2224098.16850325484753.635107187
#Sta/Elev= 30
       0 3201.13    92.8 3167.58   126.9 3157.34   138.9 3154.54   154.9 3148.55
   198.9 3137.96   206.9 3134.54   210.9 3131.29   214.9 3130.04   246.9 3127.33
   262.8 3119.39     275 3118.28     287 3119.58     295 3122.57   299.1 3122.94
   375.3  3122.2   411.4 3123.59   427.5 3122.98   435.5 3119.94   451.5 3120.63
   459.6 3119.25   479.6 3121.44   499.7 3120.84   507.2 3122.54   527.8 3130.42
   535.8  3134.4   543.8 3136.95   551.9 3142.08   563.9  3147.1   639.7  3168.5
#Mann= 4 ,-1,0
       0      .1       0   262.8    .045       0     287      .1       0
   639.7     .06       0
#XS Ineff= 3 ,-1
       0   255.6    3126     294     305 3121.06     305  575.66 3125.41
Permanent Ineff=
       F       F       F
Bank Sta=262.8,287
XS Rating Curve= 0 ,0
Exp/Cntr(USF)=0,0
Exp/Cntr=0.5,0.3

Type RM Length L Ch R = 1 ,4530    ,120.3,119.1,118.9
BEGIN DESCRIPTION:
xs 1
END DESCRIPTION:
XS GIS Cut Line= 2
2224241.85965767485398.0348667212224231.03030676484767.968358735
#Sta/Elev= 30
       0 3209.87    12.9 3202.46    20.9 3199.68    68.9 3178.17    80.9 3174.05
   117.2 3159.38   140.9 3151.32   164.9 3143.71   178.3 3140.96   188.9 3136.67
   208.9 3135.83   224.9 3130.32   244.9 3125.34   256.9 3121.24   277.8 3117.75
   292.9 3116.64   301.4 3117.75   316.9 3121.26   341.1 3121.68   380.9 3119.16
   396.9 3119.81   427.3 3119.15   472.9 3120.34   476.9 3119.88   484.9 3117.16
   516.9 3117.48   521.7 3119.36   532.9  3126.2   552.9 3135.91   630.2 3154.76
#Mann= 3 ,-1,0
       0      .1       0   277.8    .045       0   301.4      .1       0
#XS Ineff= 2 , 0
                           340.4            3125
Permanent Ineff=
       F       F
Bank Sta=277.8,301.4
XS Rating Curve= 0 ,0
Exp/Cntr=0.3,0.1

Type RM Length L Ch R = 1 ,4411    ,83.2,78.7,74.6
BEGIN DESCRIPTION:
xs 4
END DESCRIPTION:
XS GIS Cut Line= 2
2224366.13590247485374.2255919952224342.02238081484775.406470787
#Sta/Elev= 30
       0 3197.91    13.1 3191.27    53.1 3175.38    68.3 3168.06   129.2 3144.59
   141.2 3140.87   149.2 3136.19   153.2 3135.23   169.2 3134.45   185.2 3129.22
   201.2 3126.39   213.2  3125.3   225.2 3122.69   241.5  3116.3   249.2    3115
   265.3 3115.18   269.3 3116.27   277.3 3119.02   305.3 3119.43   413.4 3117.74
   433.4 3116.29   457.4 3117.12   476.2 3114.52   485.4 3116.47   497.4 3114.11
   501.5 3114.01   505.5 3115.05   517.5 3122.67   541.3  3134.8   599.3 3149.63
#Mann= 3 ,-1,0
       0      .1       0   241.5    .045       0   269.3      .1       0
#XS Ineff= 2 , 0
                          303.21         3123.49
Permanent Ineff=
       F       F
Bank Sta=241.5,269.3
XS Rating Curve= 0 ,0
Exp/Cntr(USF)=0,0
Exp/Cntr=0.5,0.3

Type RM Length L Ch R = 1 ,4332    ,22.5,21.9,21.9
BEGIN DESCRIPTION:
xs 3
END DESCRIPTION:
XS GIS Cut Line= 6
2224457.73515146 485367.562456882224446.40839893  485151.0956306
2224428.15974206485092.574075821 2224420.6085737485078.730267163
2224404.24770892485059.2230822372224394.80874848484753.400763714
#Sta/Elev= 30
       0 3194.08    18.4 3184.52    46.4 3173.84    78.5 3159.95   134.5 3139.88
   174.6 3129.54   190.6 3123.91   214.7 3121.62   231.4 3121.06   235.6 3120.09
   246.8 3114.75     252 3113.16   256.5 3112.94   264.9 3113.17     268 3114.74
   273.3 3117.81   277.5 3118.25   329.4 3118.34   365.4 3118.71   393.4 3116.12
   429.4 3116.38   445.4 3116.12   457.4 3113.54   465.4 3113.21   490.7 3113.88
   505.5 3117.52   521.5 3127.33   540.2 3135.09   597.5 3146.21   625.3 3153.61
#Mann= 5 ,-1,0
       0      .1       0   246.8    .045       0     268      .1       0
   329.4     .07       0   429.4      .1       0
#XS Ineff= 3 ,-1
       0   242.6 3120.44     272     336 3118.33     336     600 3121.08
Permanent Ineff=
       F       F       F
Bank Sta=246.8,268
XS Rating Curve= 0 ,0
Exp/Cntr(USF)=0,0
Exp/Cntr=0.5,0.3

Type RM Length L Ch R = 1 ,4310    ,113.8,117.8,121.3
BEGIN DESCRIPTION:
xs 2
END DESCRIPTION:
XS GIS Cut Line= 6
2224479.13012848 485365.045400762224469.69116803485154.241950749
2224447.66692699485083.1351153732224438.22796654485066.774250596
2224421.86710176485049.7841217892224412.42814131484769.132364461
#Sta/Elev= 30
       0 3192.77    75.9 3159.05      84 3157.38   103.9 3148.95   119.9 3143.29
   168.9 3129.22     188 3122.79   208.1 3120.65   237.3 3119.95   243.83114.256
   245.7 3113.01   249.9 3112.73   262.4 3112.81   267.5  3114.2   270.8 3117.48
     275 3118.24   324.6 3118.51   372.4 3118.25   392.6 3115.32   428.6 3115.82
   444.6 3115.91   452.6 3112.62   472.7 3113.04   488.7 3115.83   504.4 3116.89
   512.2 3119.57   524.7 3126.54   544.7 3132.39   568.7 3141.09   608.8 3148.85
#Mann= 5 ,-1,0
       0      .1       0   243.8    .045       0   267.5      .1       0
   324.6     .07       0   428.6      .1       0
#XS Ineff= 3 ,-1
       0  240.28  3118.5  269.47     360  3116.9     360   560.3 3119.06
Permanent Ineff=
       F       F       F
Bank Sta=243.8,267.5
XS Rating Curve= 0 ,0
Exp/Cntr(USF)=0,0
Exp/Cntr=0.5,0.3

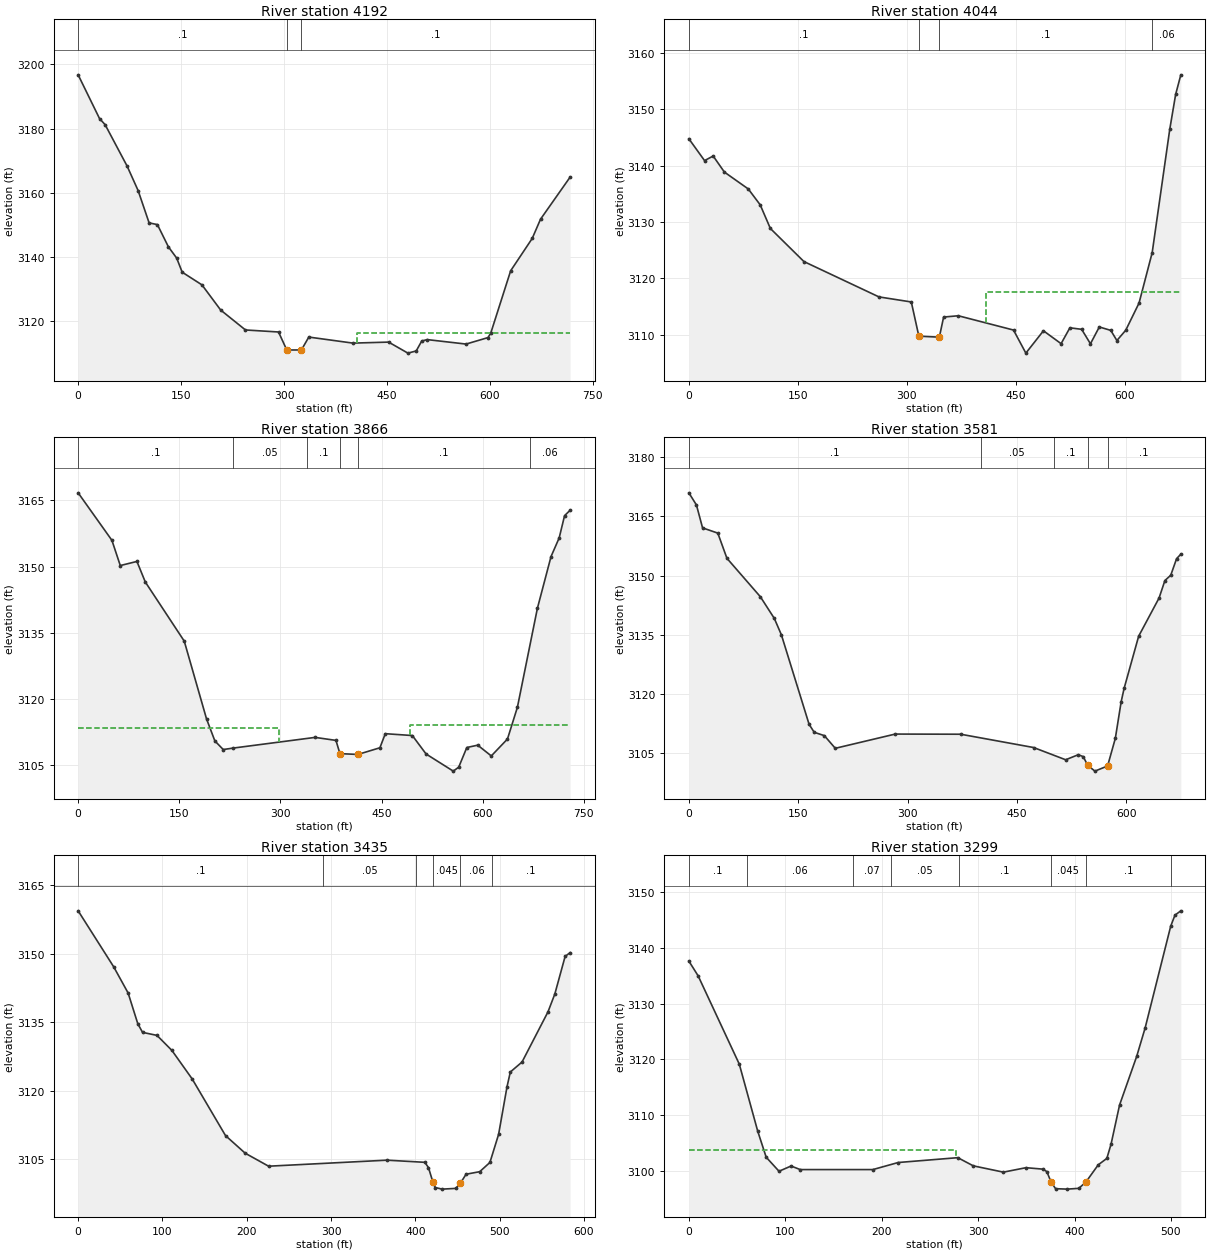
Type RM Length L Ch R = 1 ,4192    ,149,148.8,147.6
XS GIS Cut Line= 3
2224596.98886204485412.3301940922224558.35246819484900.784339501
2224535.17063188484698.329635721
#Sta/Elev= 30
       0 3196.75    31.2 3183.12    39.3 3181.24    71.4 3168.32    87.4 3160.71
   103.4 3150.66   115.5 3150.12   131.5 3143.21   143.6 3139.69   151.6 3135.31
   180.4 3131.36   207.7 3123.52   243.8 3117.32     292 3116.69     304 3111.08
   325.3  3111.1   336.1 3115.11   400.3 3113.23   452.4 3113.54   480.5 3110.11
   492.6 3110.79   500.6 3113.87   508.6 3114.32   565.2 3112.93   597.2 3114.95
   601.2 3116.35   630.2 3135.75   661.6 3145.82   673.7  3151.8   716.8  3164.9
#Mann= 3 ,0,0
       0      .1       0     304    .045       0   325.3      .1       0
#XS Ineff= 2 , 0
                          406.32         3116.24
Permanent Ineff=
       F       F
Bank Sta=304,325.3
XS Rating Curve= 0 ,0
Exp/Cntr(USF)=0,0
Exp/Cntr=0.3,0.1

Type RM Length L Ch R = 1 ,4044    ,190.8,178.2,165.5
XS GIS Cut Line= 3
2224870.99996955485336.953071578 2224735.9333759485192.238864089
2224665.64361797484718.127555744
#Sta/Elev= 30
       0 3144.79    21.6 3140.91    33.5 3141.72    48.9 3138.87    81.8 3135.87
    98.2 3133.05   112.2 3128.85   158.4 3122.97   261.7 3116.69   306.2 3115.79
   316.6 3109.71   344.8 3109.54   350.7 3113.11   370.9 3113.34   446.9  3110.8
   463.9  3106.7   488.1 3110.67   512.4 3108.38   524.5  3111.2   540.7 3110.93
   552.8 3108.36     565 3111.35   580.8 3110.74   589.2 3108.94   601.4 3110.77
   619.7  3115.6   637.8 3124.56     662 3146.49   670.1 3152.68   677.2 3156.15
#Mann= 4 ,-1,0
       0      .1       0   316.6    .045       0   344.8      .1       0
  637.95     .06       0
#XS Ineff= 2 , 0
                          408.56         3117.49
Permanent Ineff=
       F       F
Bank Sta=316.6,344.8
XS Rating Curve= 0 ,0
Exp/Cntr(USF)=0,0
Exp/Cntr=0.3,0.1

Type RM Length L Ch R = 1 ,3866    ,261.6,284.1,294.7
XS GIS Cut Line= 4
2224998.80735809485373.6938002412224909.17092436485022.875344071
2224836.53450392484956.4207466472224805.62538884484689.056901196
#Sta/Elev= 30
       0 3166.73    50.1 3155.97    62.5 3150.26    87.2 3151.19    99.6 3146.54
   157.4 3133.14   190.4 3115.55   202.8 3110.54   215.2 3108.59     230 3108.92
   351.5 3111.34   382.4 3110.66   388.3 3107.66     415 3107.48   447.6 3108.99
   455.6 3112.18   495.7 3111.76   516.1 3107.58   556.4  3103.7   564.5  3104.6
   576.5 3109.05   592.7 3109.58   612.8 3107.14   636.8 3110.97   651.5 3118.14
   681.2 3140.58   701.4 3152.29   713.5 3156.52   721.5 3161.56   729.7 3162.78
#Mann= 6 ,-1,0
       0      .1       0     230     .05       0     340      .1       0
   388.3    .045       0     415      .1       0  670.54     .06       0
#XS Ineff= 2 , 0
          297.46 3113.45  491.72         3114.16
Permanent Ineff=
       F       F
Bank Sta=388.3,415
XS Rating Curve= 0 ,0
Exp/Cntr(USF)=0,0
Exp/Cntr=0.3,0.1

Type RM Length L Ch R = 1 ,3581    ,151.1,146.5,142.8
XS GIS Cut Line= 3
2225088.03323421485339.1814613532224987.75494763485003.467197573
2224997.92810713484679.379401803
#Sta/Elev= 30
       0 3170.98    10.4  3167.9    18.8 3162.09    39.7 3160.76    52.2 3154.38
    98.1 3144.61   117.2 3139.12   126.9 3134.96   164.9 3112.25   171.9 3110.24
   185.8 3109.39   200.8 3106.18     283 3109.79   372.7 3109.75   472.7 3106.38
   516.7 3103.27   534.1 3104.56   540.8 3104.06     547 3101.84   556.8 3100.39
   574.2  3101.7   584.8  3108.7   592.8 3117.99   596.8 3121.35   616.8 3134.62
   644.8 3144.31   652.8 3148.74   660.8 3150.08   668.8 3154.28   674.6 3155.41
#Mann= 5 ,-1,0
       0      .1       0  400.37     .05       0  500.37      .1       0
     547    .045       0   574.2      .1       0
Bank Sta=547,574.2
XS Rating Curve= 0 ,0
Exp/Cntr(USF)=0,0
Exp/Cntr=0.3,0.1

Type RM Length L Ch R = 1 ,3435    ,142.1,135.9,130.6
XS GIS Cut Line= 3
2225279.94569436 485216.69049526 2225152.4346928484878.784848721
2225116.59906145484659.372652261
#Sta/Elev= 30
       0 3159.41    42.2 3147.14    59.3 3141.41    70.8 3134.67    76.4  3132.8
    93.5 3132.14   111.2 3128.85   135.3 3122.59   174.8  3110.2   198.1 3106.35
   225.9  3103.5   366.3 3104.82   411.2 3104.35   415.5  3103.2   420.9 3099.95
   423.6 3098.83   431.7 3098.48   447.9 3098.64   453.4 3099.78   460.1 3101.74
   476.3  3102.3   488.4 3104.32   498.7 3110.47   508.7 3120.91   512.6 3124.12
   526.5 3126.31   557.3  3137.3   565.4 3141.21   577.6 3149.43   583.5 3150.26
#Mann= 6 ,-1,0
       0      .1       0     290     .05       0  401.16     .06       0
   420.9    .045       0   453.4     .06       0  491.16      .1       0
Bank Sta=420.9,453.4
XS Rating Curve= 0 ,0
Exp/Cntr(USF)=0,0
Exp/Cntr=0.3,0.1

Type RM Length L Ch R = 1 ,3299    ,116,115.4,114.6
XS GIS Cut Line= 2
2225429.07012811485105.8703360842225213.03732834484643.660624958
#Sta/Elev= 30
       0 3137.64     9.6 3134.99    52.3 3119.13    71.4  3107.1    80.2 3102.41
    93.5 3099.89     106 3100.83   115.5 3100.19   190.8 3100.19   217.1 3101.46
   278.9 3102.33     295 3100.86   326.2 3099.73   349.6 3100.53   367.2 3100.27
   371.3 3099.82  375.453098.024   380.3 3096.76   392.4 3096.68   404.4 3096.82
   411.73097.939   424.6 3101.05   433.5  3102.2   437.9 3104.79   446.7  3111.8
   464.4  3120.5   473.2 3125.63   499.7 3143.89   504.1 3145.88   510.2 3146.66
#Mann= 8 ,-1,0
       0      .1       0      60     .06       0     170     .07       0
     210     .05       0     280      .1       0  375.45    .045       0
   411.7      .1       0     500     .06       0
#XS Ineff= 2 , 0
          277.14 3103.78
Permanent Ineff=
       F       F
Bank Sta=375.45,411.7
XS Rating Curve= 0 ,0
Exp/Cntr(USF)=0,0
Exp/Cntr=0.3,0.1

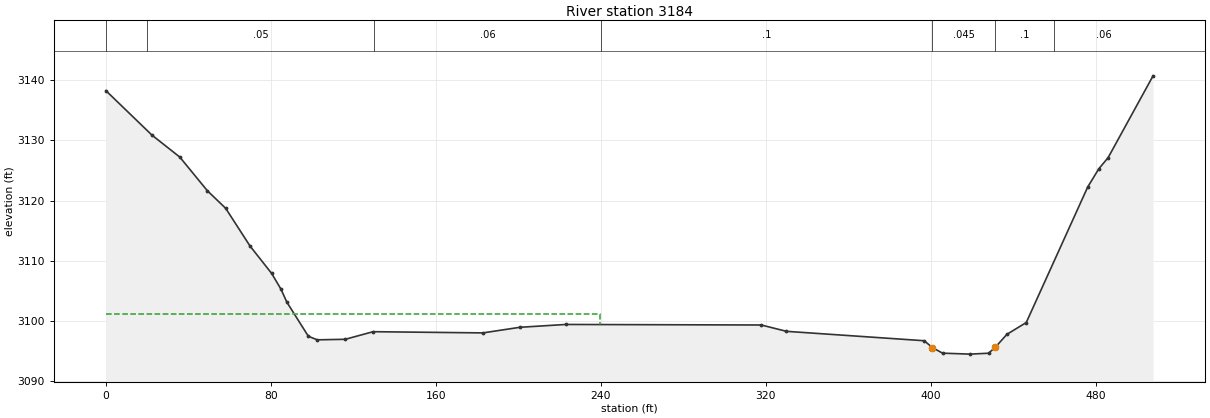
Type RM Length L Ch R = 1 ,3184    ,120.3,120.1,119.9
XS GIS Cut Line= 2
2225545.61010713485065.3135482362225321.33410385484609.584709584
#Sta/Elev= 30
       0 3138.22    22.4 3130.83    35.8 3127.22    49.2 3121.63    58.1 3118.71
    69.9 3112.46    80.4 3107.91    84.9 3105.31    87.8 3103.13    98.2 3097.49
   102.5  3096.9   116.1 3096.99   129.6 3098.25   182.9 3098.05   200.8 3098.98
   223.1 3099.45   317.9 3099.36   330.1 3098.31   396.9 3096.75  400.87 3095.62
   405.8 3094.69   419.2 3094.53   428.1 3094.68   431.4 3095.67     437 3097.81
   446.4 3099.77   476.2 3122.24   481.6 3125.27   486.1 3127.11   507.9 3140.68
#Mann= 7 ,-1,0
       0      .1       0      20     .05       0     130     .06       0
     240      .1       0  400.87    .045       0   431.4      .1       0
     460     .06       0
#XS Ineff= 2 , 0
          239.64 3101.24
Permanent Ineff=
       F       F
Bank Sta=400.87,431.4
XS Rating Curve= 0 ,0
Exp/Cntr(USF)=0,0
Exp/Cntr=0.3,0.1