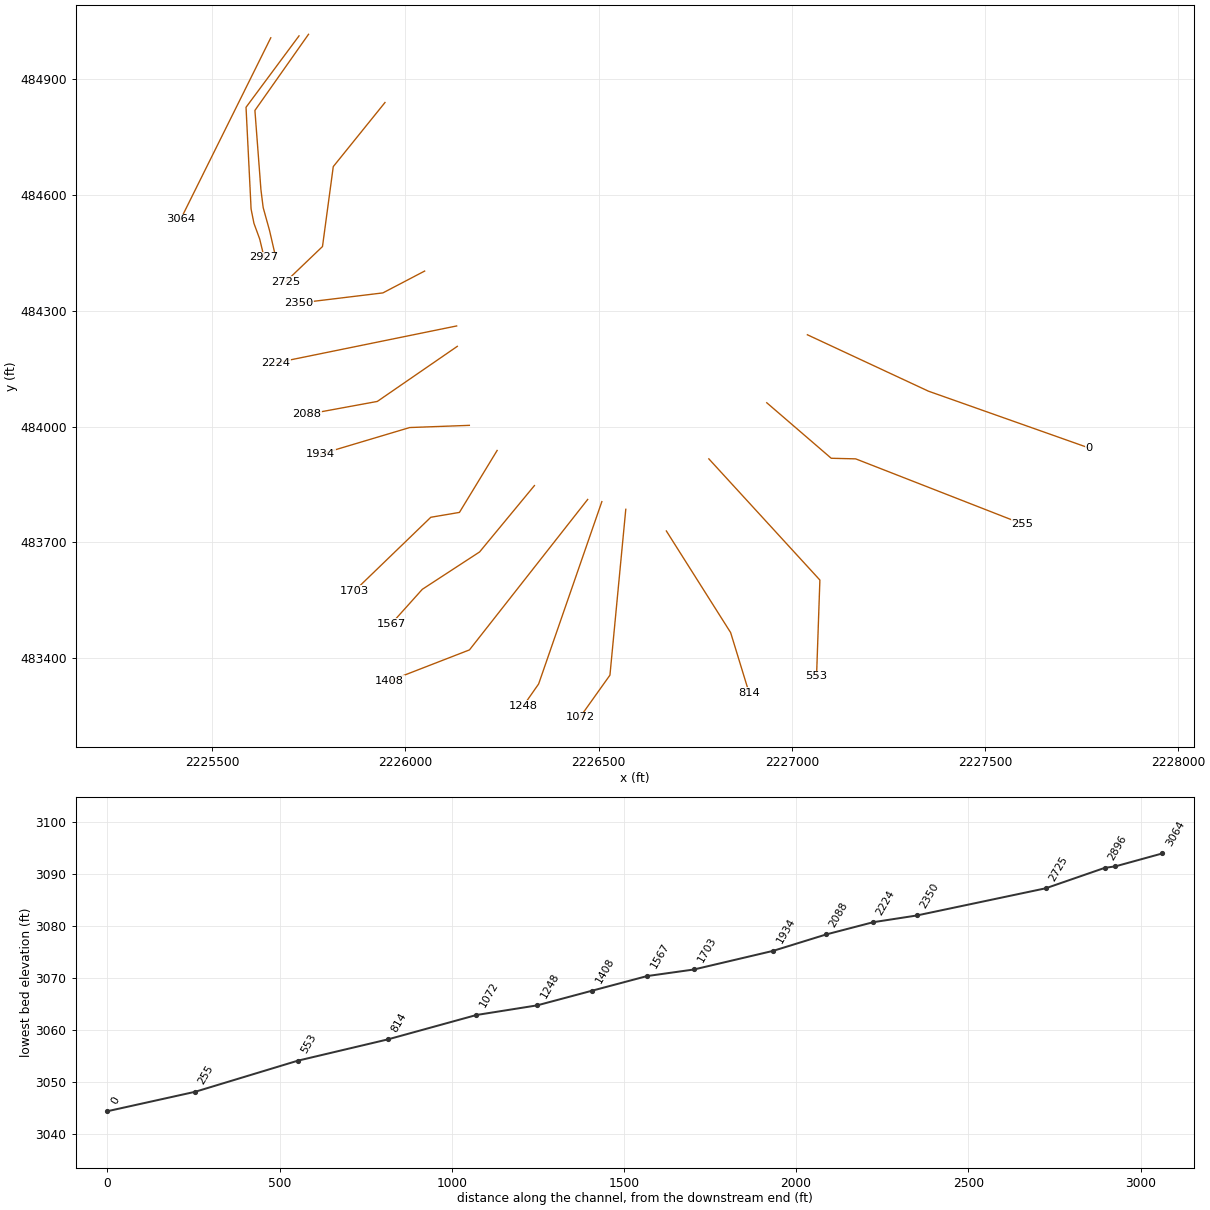
HEC-RAS study CRKDFK.prj: CRKDFK

--- CRKDFK.g01 (geometry) --- (continued)

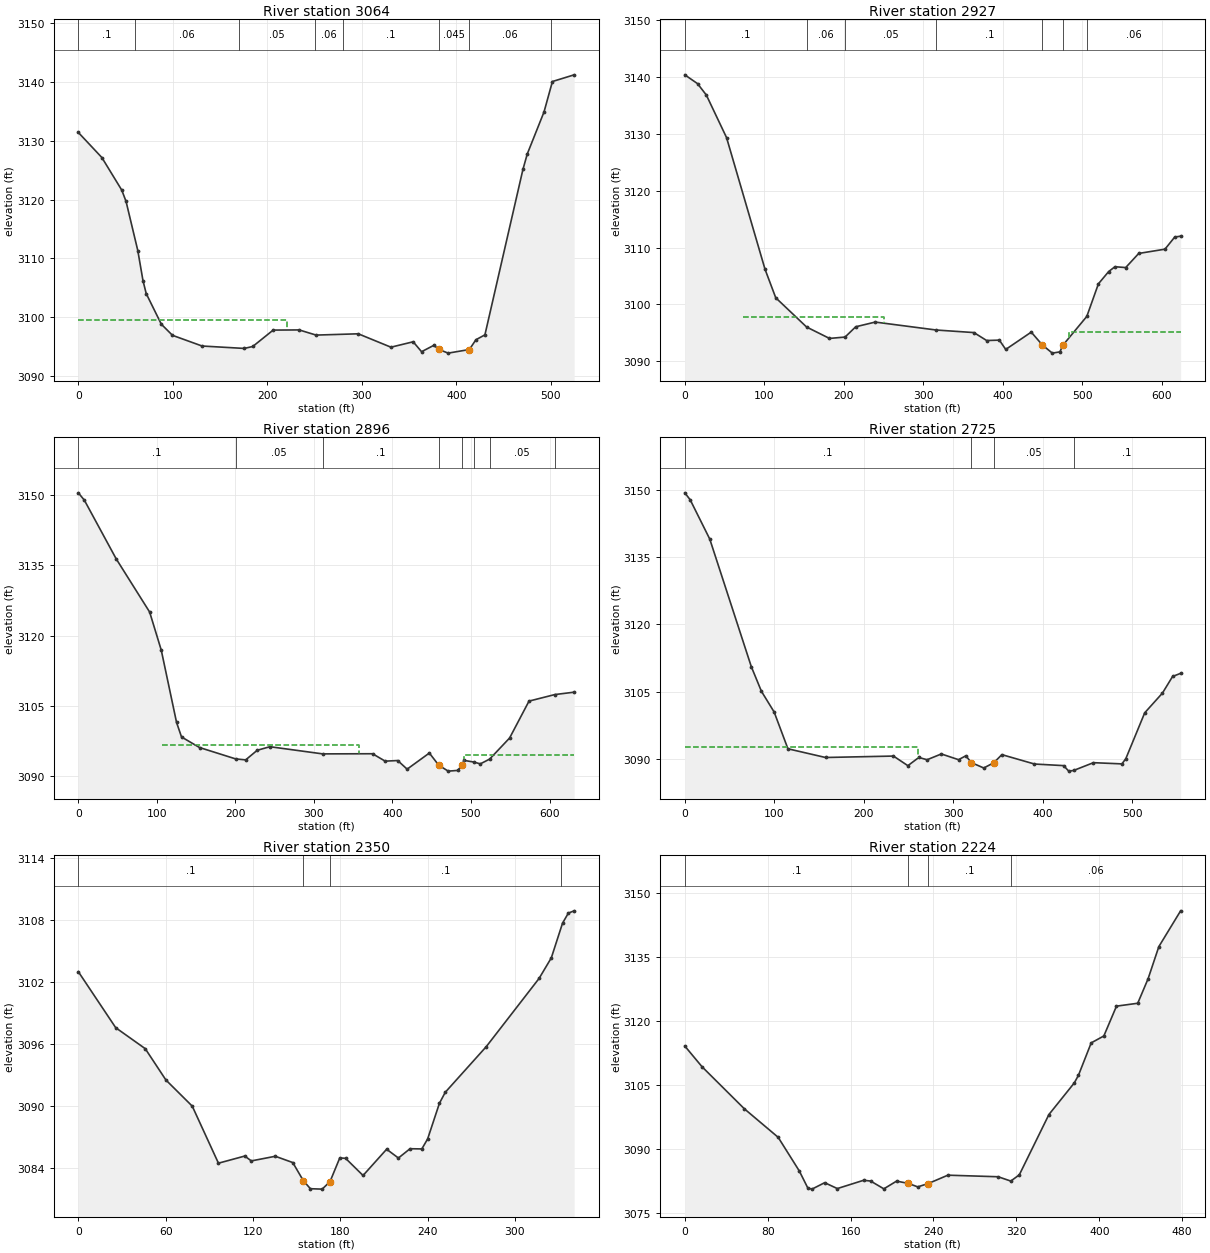
Type RM Length L Ch R = 1 ,3064    ,127.2,136.3,145.7
BEGIN DESCRIPTION:
xs 4
END DESCRIPTION:
XS GIS Cut Line= 2
2225651.23356371485006.4124466852225417.97909511484536.618235291
#Sta/Elev= 30
       0 3131.44    24.9 3127.17      46 3121.61    50.5 3119.69    62.9 3111.34
    68.4 3106.21    71.8 3104.02    87.8  3098.8    99.6 3096.91   130.9 3095.09
   175.5 3094.68   184.5 3095.01   206.1  3097.8   233.6 3097.83   251.5 3096.95
   296.1 3097.17   330.7 3094.89   354.2 3095.81   363.1 3094.12   376.2 3095.22
     381 3094.53   391.2 3093.88  413.623094.492   420.6 3096.16   430.1 3096.99
   470.3 3125.14   474.9 3127.78   492.6 3134.92   501.5 3140.11   524.5 3141.25
#Mann= 8 ,-1,0
       0      .1       0      60     .06       0     170     .05       0
     250     .06       0     280      .1       0     381    .045       0
  413.62     .06       0     500      .1       0
#XS Ineff= 2 , 0
          220.68 3099.46
Permanent Ineff=
       F       F
Bank Sta=381,413.62
XS Rating Curve= 0 ,0
Exp/Cntr(USF)=0,0
Exp/Cntr=0.5,0.3

Type RM Length L Ch R = 1 ,2927    ,29.6,31.6,33.3
BEGIN DESCRIPTION:
xs 3
END DESCRIPTION:
XS GIS Cut Line= 6
2225724.33091478485011.340357993 2225587.1707167484826.543683931
2225600.31181352484562.9004289352225607.70368048484525.941094123
2225622.48741441484485.6964851052225633.98587413484438.060009124
#Sta/Elev= 30
       0 3140.42      16 3138.87    27.1 3136.86    52.5 3129.37   100.9 3106.18
   114.4 3101.15   153.2    3096     182 3093.99   201.6 3094.23     215 3096.04
   239.5 3096.87   316.3 3095.47   363.7 3095.02   379.7 3093.62   395.7 3093.69
   403.7 3092.05   435.8  3095.1   449.8 3092.83   462.3  3091.4   471.8 3091.62
   475.8 3092.83   505.7 3097.87   520.3 3103.61   533.2 3105.77   541.1 3106.62
   554.6 3106.47     571 3108.96     604 3109.71   616.3 3111.85   623.7    3112
#Mann= 7 ,-1,0
       0      .1       0   153.2     .06       0   201.6     .05       0
   316.3      .1       0   449.8    .045       0   475.8      .1       0
   505.7     .06       0
#XS Ineff= 3 ,-1
   73.78  250.07 3097.83  250.07   442.7  3093.3   482.8 623.677  3095.1
Permanent Ineff=
       F       F       F
Bank Sta=449.8,475.8
XS Rating Curve= 0 ,0
Exp/Cntr(USF)=0,0
Exp/Cntr=0.5,0.3

Type RM Length L Ch R = 1 ,2896    ,176.2,170.9,165.8
BEGIN DESCRIPTION:
xs 2
END DESCRIPTION:
XS GIS Cut Line= 6
2225748.97047132 485015.446950752225610.16763614484818.330498417
2225625.77268861 484613.000860572225631.52191847484567.007021692
 2225647.9482895484507.8720859922225665.19597908484433.132097816
#Sta/Elev= 30
       0 3150.49     7.7 3148.91    48.1 3136.43    90.8 3125.05   105.6 3116.92
   125.1 3101.48   131.4 3098.39   154.3 3096.14   200.3 3093.71   213.1  3093.5
   227.8 3095.55     244 3096.31   311.1 3094.78   374.7 3094.81   390.7 3093.23
   406.7 3093.36   418.7 3091.52     447 3094.96   458.9 3092.37     471  3091.1
   483.1 3091.25   488.4 3092.32   491.2 3093.39   503.6 3093.04   511.9 3092.65
   523.8 3093.67   549.2 3098.17   573.9 3106.04   606.8 3107.44   631.4 3107.95
#Mann= 8 ,-1,0
       0      .1       0   200.3     .05       0   311.1      .1       0
   458.9    .045       0   488.4      .1       0   503.6     .06       0
   523.8     .05       0   606.8      .1       0
#XS Ineff= 3 ,-1
  106.06  357.32 3096.71  357.32  455.49 3093.11  490.55  630.75  3094.6
Permanent Ineff=
       F       F       F
Bank Sta=458.9,488.4
XS Rating Curve= 0 ,0
Exp/Cntr(USF)=0,0
Exp/Cntr=0.5,0.3

Type RM Length L Ch R = 1 ,2725    ,394.2,374.5,349.7
BEGIN DESCRIPTION:
xs 1
END DESCRIPTION:
XS GIS Cut Line= 4
2225946.90824221484838.8634622022225813.03331833484672.957114821
2225785.10848758484465.9848398722225689.83553562484374.818480667
#Sta/Elev= 30
       0 3149.45       6  3147.9    27.9  3139.1    74.3 3110.56    85.6 3105.05
    99.8 3100.42   115.2 3092.19   157.2 3090.24   233.1 3090.56   249.2 3088.41
   261.4 3090.24   270.7 3089.74   286.6 3091.03   305.8 3089.75   313.9 3090.61
  320.253089.086     334 3087.89   345.3 3089.08   354.2 3090.88   390.6 3088.78
   423.2 3088.42   428.9 3087.19   434.4 3087.34   456.5 3089.08   488.3 3088.81
   492.6 3089.94   513.8 3100.24   533.6 3104.65   544.9 3108.36   553.9 3109.07
#Mann= 4 ,-1,0
       0      .1       0  320.25    .045       0   345.3     .05       0
   434.4      .1       0
#XS Ineff= 2 , 0
          260.62 3092.59
Permanent Ineff=
       F       F
Bank Sta=320.25,345.3
XS Rating Curve= 0 ,0
Exp/Cntr(USF)=0,0
Exp/Cntr=0.3,0.1

Type RM Length L Ch R = 1 ,2350    ,125,126.7,127.4
XS GIS Cut Line= 3
2226049.53642511484402.5077321972225941.52002522484345.987522957
2225724.23122081484319.611425311
#Sta/Elev= 30
       0 3103.01    25.7 3097.59      46 3095.56    60.2 3092.53    78.3    3090
    96.3 3084.48   114.4 3085.17   118.9  3084.7   135.4 3085.15   147.4 3084.54
   154.6  3082.8   159.5 3082.01   167.6 3081.97     173  3082.7   179.7 3084.99
   183.7 3084.95   195.7 3083.29   211.9 3085.83     220 3084.98     228 3085.88
   236.1 3085.86   240.1 3086.83   248.2 3090.28   252.2 3091.34   280.4 3095.76
   316.7 3102.36   325.1 3104.35   332.8  3107.7   336.8 3108.68   340.8  3108.9
#Mann= 4 ,-1,0
       0      .1       0   154.6    .045       0     173      .1       0
  331.91     .06       0
Bank Sta=154.6,173
XS Rating Curve= 0 ,0
Exp/Cntr(USF)=0,0
Exp/Cntr=0.3,0.1

Type RM Length L Ch R = 1 ,2224    ,128.9,136,140.1
XS GIS Cut Line= 2
2226132.43273199484260.4190944032225663.54644527 484164.74373819
#Sta/Elev= 30
       0 3114.23    16.6 3109.38    57.4 3099.53    90.1 3092.83   110.5 3084.94
   118.7 3080.95   122.7 3080.68     135 3082.19   147.2 3080.81   172.5 3082.75
   179.3 3082.58   192.1 3080.75   204.4 3082.56   215.7 3082.02   224.8 3081.21
  234.91 3081.99   253.9 3083.95   302.4 3083.58   314.6 3082.57   322.8 3084.02
   351.4 3098.17   375.9 3105.59   379.9 3107.37   392.2 3114.97   404.4 3116.59
   416.6 3123.58   437.1 3124.26   447.1    3130   457.5 3137.55   478.5 3145.93
#Mann= 4 ,-1,0
       0      .1       0   215.7    .045       0  234.91      .1       0
   314.6     .06       0
Bank Sta=215.7,234.91
XS Rating Curve= 0 ,0
Exp/Cntr(USF)=0,0
Exp/Cntr=0.3,0.1

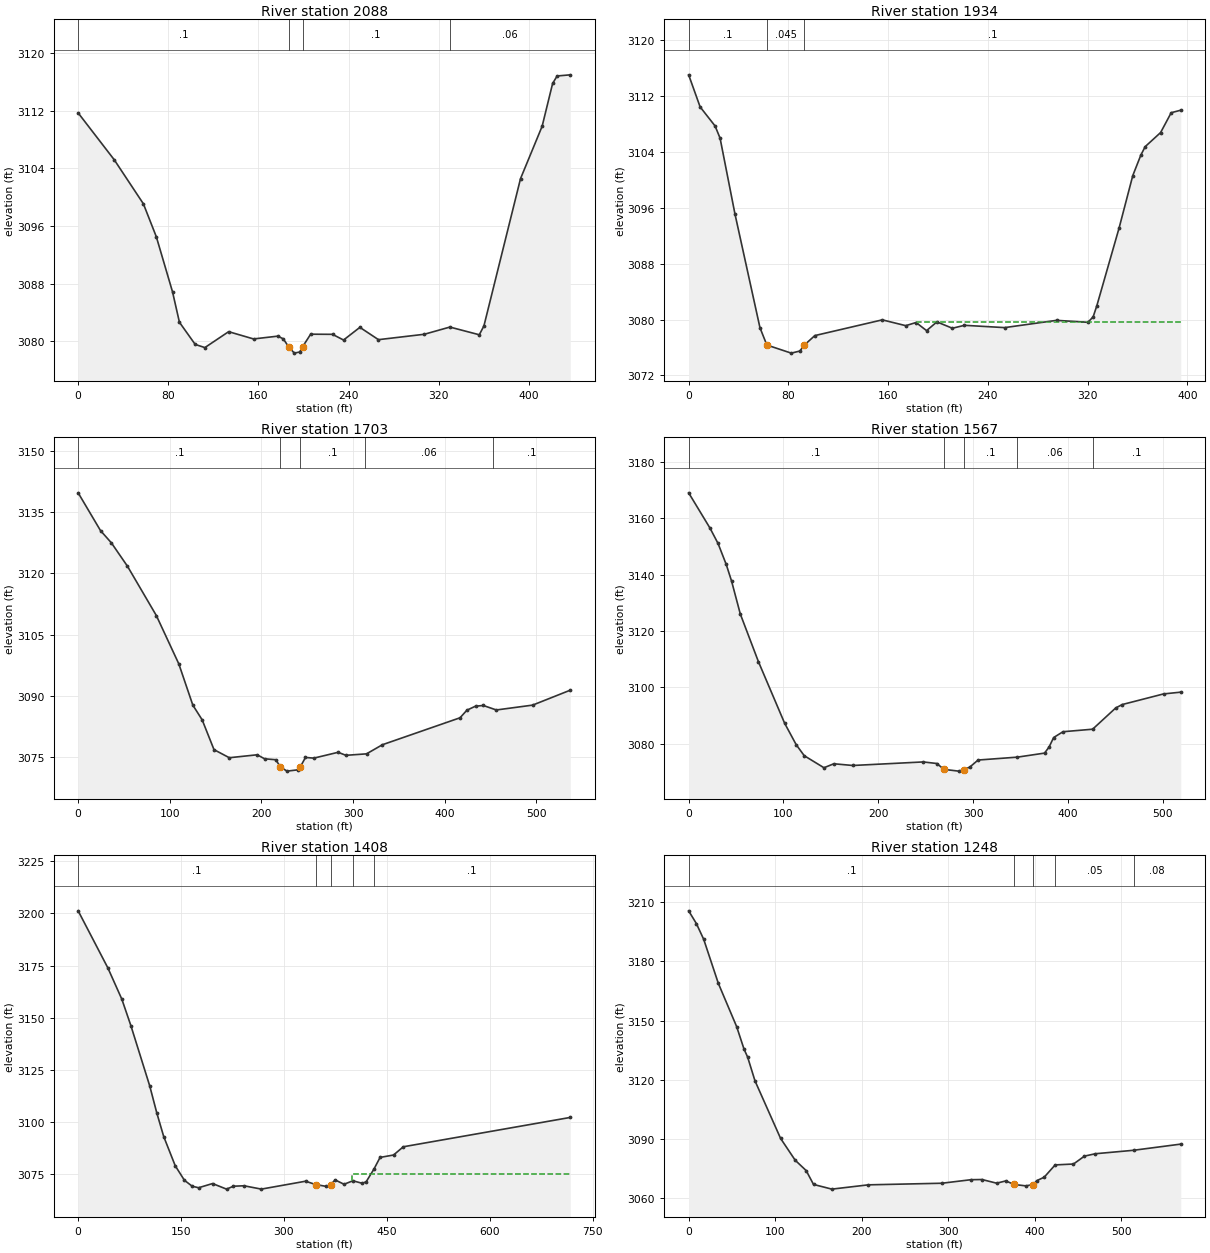
Type RM Length L Ch R = 1 ,2088    ,169.9,154.1,141.3
XS GIS Cut Line= 3
2226134.18697113484207.6483328422225927.03891984484065.001471171
 2225744.6990184484031.510468866
#Sta/Elev= 30
       0  3111.7      32  3105.2    57.9 3099.08    69.4  3094.5    83.8 3086.84
    89.9 3082.63   103.9 3079.55   112.5 3079.11   133.6 3081.32   155.7 3080.31
   177.3  3080.7   182.1 3080.32     187 3079.19   191.9 3078.34   196.7  3078.5
  199.18 3079.21   206.4 3080.97   225.8 3080.95   235.6 3080.16   250.1 3081.92
   266.6 3080.21   307.3 3080.96     330 3081.96   356.1 3080.89   360.2 3082.11
   392.7 3102.57   411.9 3109.85   421.2 3115.79   425.2 3116.83   436.9 3116.99
#Mann= 4 ,-1,0
       0      .1       0     187    .045       0  199.18      .1       0
     330     .06       0
Bank Sta=187,199.18
XS Rating Curve= 0 ,0
Exp/Cntr(USF)=0,0
Exp/Cntr=0.3,0.1

Type RM Length L Ch R = 1 ,1934    ,228.5,230.3,232.7
XS GIS Cut Line= 3
2226165.32545925 484003.079152332226010.91657693483997.406779684
2225780.80796964483928.692670204
#Sta/Elev= 30
       0 3115.01     9.2 3110.42    21.2 3107.69    25.2 3105.95    37.2 3095.05
    57.2 3078.82   62.71 3076.35    82.3 3075.19    89.2 3075.49    92.63076.314
   101.2  3077.7   155.3 3079.95   174.1 3079.12   182.4 3079.57   190.8 3078.41
   199.1 3079.66   211.5 3078.75   221.2 3079.17   253.4 3078.84   295.1 3079.88
   320.2  3079.6   324.4 3080.38   327.3 3081.94   345.2 3093.09   356.2  3100.6
   362.6  3103.5   366.1 3104.73   378.5 3106.75     387 3109.59   394.7 3109.95
#Mann= 3 ,0,0
       0      .1       0   62.71    .045       0    92.6      .1       0
#XS Ineff= 2 , 0
                          182.75         3079.61
Permanent Ineff=
       F       F
Bank Sta=62.71,92.6
XS Rating Curve= 0 ,0
Exp/Cntr(USF)=0,0
Exp/Cntr=0.3,0.1

Type RM Length L Ch R = 1 ,1703    ,129,135.9,142
XS GIS Cut Line= 4
2226237.24343645483938.0531557692226139.64220689483777.702010691
2226065.54416568483765.1255947242225868.36925168483574.772272786
#Sta/Elev= 30
       0 3139.74    24.4 3130.49    36.3 3127.48    53.8 3121.77    85.3  3109.7
   109.8 3097.87   125.1 3087.77   135.3 3084.16   148.2 3076.87   164.9 3074.89
   195.3 3075.61   203.4 3074.63   215.6  3074.4   220.6 3072.65   227.8 3071.61
   239.9 3071.93  242.35 3072.65     248 3074.96   257.1 3074.79   283.6 3076.22
   292.1 3075.48   314.6 3075.84   331.9 3078.07   416.6 3084.67   424.1 3086.53
   433.5 3087.51     442 3087.68   456.2 3086.58   495.8 3087.77   536.9 3091.43
#Mann= 5 ,-1,0
       0      .1       0   220.6    .045       0  242.35      .1       0
  312.88     .06       0  452.88      .1       0
Bank Sta=220.6,242.35
XS Rating Curve= 0 ,0
Exp/Cntr(USF)=0,0
Exp/Cntr=0.3,0.1

Type RM Length L Ch R = 1 ,1567    ,152.6,158.8,162.9
XS GIS Cut Line= 4
2226333.82993778483847.2101630742226191.86157901483675.401321248
 2226043.5634208483578.6458155882225963.98879933483490.028623488
#Sta/Elev= 30
       0 3169.01    22.5 3156.51      31 3151.06    39.6 3143.65    45.2 3137.79
    54.5 3126.03    73.6 3109.14   101.2 3087.34   113.4 3079.73   121.9 3075.82
   142.7 3071.55   153.1 3072.96   173.1 3072.35   247.4 3073.61   261.8 3073.05
   269.1 3070.98   284.6 3070.35   290.7 3070.91   296.6 3071.82   305.2 3074.28
   346.7 3075.31   375.3 3076.74   380.1  3078.9   384.9 3082.26   394.8 3084.32
     426 3085.21   450.3 3092.73   457.2 3093.95   500.8 3097.72     519 3098.35
#Mann= 5 ,-1,0
       0      .1       0   269.1    .045       0   290.7      .1       0
   346.7     .06       0     426      .1       0
Bank Sta=269.1,290.7
XS Rating Curve= 0 ,0
Exp/Cntr(USF)=0,0
Exp/Cntr=0.3,0.1

Type RM Length L Ch R = 1 ,1408    ,154.3,160.4,165
XS GIS Cut Line= 3
 2226471.6266917483811.238032896 2226165.6264524483421.783182875
2225958.53538136483341.419483664
#Sta/Elev= 30
       0 3201.28    43.3 3173.86    63.7 3158.81    76.8 3146.18   104.4 3117.09
   114.5 3104.33   124.7 3092.84   141.5  3078.8   154.9 3071.81   166.3 3068.94
   175.6 3068.23   195.9 3070.24   216.3 3067.56   226.4 3068.96   241.7 3069.17
   267.1 3067.57   331.5 3071.36   346.53069.734   361.7 3068.88   368.2 3069.72
   374.6 3071.98   387.6  3069.9   400.5 3071.57   414.1 3070.36   419.8 3071.08
   431.2  3077.2   440.1  3082.8   459.7 3083.95     474 3087.91   717.4 3102.01
#Mann= 5 ,-1,0
       0      .1       0   346.5    .045       0   368.2      .1       0
   400.5     .06       0   431.2      .1       0
#XS Ineff= 2 , 0
                           399.9            3075
Permanent Ineff=
       F       F
Bank Sta=346.5,368.2
XS Rating Curve= 0 ,0
Exp/Cntr(USF)=0,0
Exp/Cntr=0.3,0.1

Type RM Length L Ch R = 1 ,1248    ,168.1,176.4,180.4
XS GIS Cut Line= 3
 2226508.3515508483805.6143382112226344.68102253483333.592151719
2226304.89371179483276.623956798
#Sta/Elev= 30
       0 3205.53     8.9 3199.11    17.4 3191.12    34.3 3168.86    55.5 3146.95
      64  3135.6    68.2 3131.53    76.7 3119.52   106.3  3090.4   123.2 3079.35
   135.9 3074.11   144.4  3067.1   165.6 3064.73   207.8  3066.9   292.8 3067.71
   326.5  3069.5   339.2 3069.59   356.1 3067.74   366.8 3068.88   376.3 3067.09
     390 3066.37   398.4 3067.07   402.7 3069.05   411.1 3070.75   423.8 3076.98
     445 3077.43   457.7 3081.43   470.4 3082.64   514.4 3084.38   569.1 3087.51
#Mann= 5 ,-1,0
       0      .1       0   376.3    .045       0   398.4     .06       0
   423.8     .05       0   514.4     .08       0
Bank Sta=376.3,398.4
XS Rating Curve= 0 ,0
Exp/Cntr(USF)=0,0
Exp/Cntr=0.3,0.1

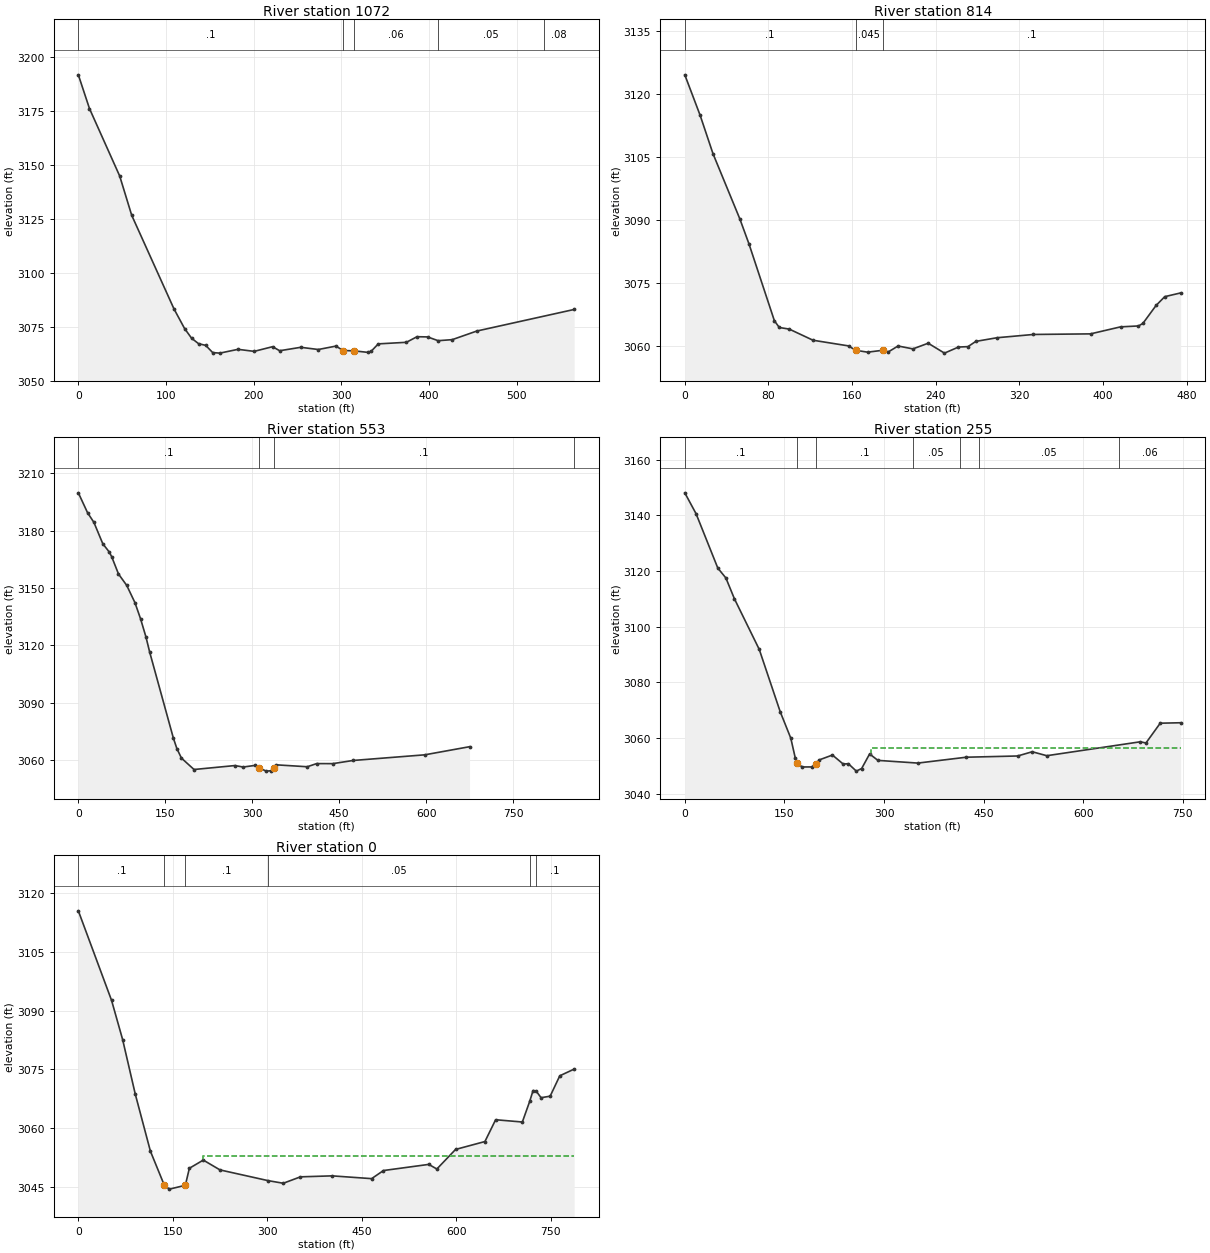
Type RM Length L Ch R = 1 ,1072    ,248.3,257.3,264.9
XS GIS Cut Line= 3
2226570.29515113483785.8039454622226529.29580525483356.369283569
2226451.39023267483246.995780209
#Sta/Elev= 30
       0 3191.93    12.7  3176.3    47.2    3145    60.9 3126.79   109.1 3083.41
   121.2  3074.3   129.2  3069.8   137.2 3067.25   145.3 3066.48   153.3 3063.13
   161.4 3062.88   182.2 3064.64   200.6  3063.7   221.6 3065.86   229.7 3063.99
   253.8 3065.58   273.8 3064.56     294 3066.15     302 3064.08   314.3 3063.95
   330.1 3063.24   334.1 3063.73   342.2 3067.17   374.3  3067.9   386.4 3070.49
   398.4  3070.4   410.5 3068.65   426.6 3069.13   454.6 3073.12   565.7 3083.13
#Mann= 5 ,-1,0
       0      .1       0     302    .045       0   314.3     .06       0
     410     .05       0  531.39     .08       0
Bank Sta=302,314.3
XS Rating Curve= 0 ,0
Exp/Cntr(USF)=0,0
Exp/Cntr=0.3,0.1

Type RM Length L Ch R = 1 ,814     ,257.6,261.1,264.3
XS GIS Cut Line= 3
2226675.34104633483729.6142765882226841.75411556483466.585867747
2226889.53461219483310.679049983
#Sta/Elev= 30
       0 3124.54    14.7 3114.87      27 3105.72    52.6 3090.23    61.4 3084.23
    85.7 3065.92    90.4 3064.31    99.9 3063.93   122.7 3061.27   156.7 3059.92
   163.3 3058.88   174.9 3058.43   189.4 3058.88   194.6 3058.48     204  3059.9
   218.2 3059.21   232.8 3060.56   248.4  3058.2   261.8 3059.65   270.9 3059.75
   278.4    3061   298.7 3061.87   333.5 3062.65   388.1 3062.79   416.8 3064.46
     434 3064.68   438.2 3065.28   450.8 3069.56   459.1 3071.66   474.3 3072.55
#Mann= 3 ,0,0
       0      .1       0   163.3    .045       0   189.4      .1       0
Bank Sta=163.3,189.4
XS Rating Curve= 0 ,0
Exp/Cntr(USF)=0,0
Exp/Cntr=0.3,0.1

Type RM Length L Ch R = 1 ,553     ,293,298.3,295.4
XS GIS Cut Line= 3
2226785.35420978483916.3290241712227072.80898003483602.601506099
2227064.14258997483353.258123402
#Sta/Elev= 30
       0 3199.76      16  3189.3    26.9 3184.28    42.2 3173.11    53.1 3168.89
    57.5 3166.37    69.3 3157.28    83.5 3151.32    97.7 3142.28   107.4 3133.81
   116.7  3124.3   123.1 3116.41     164 3071.38     170 3065.94   177.9 3060.94
   199.6 3054.97   270.1 3057.03   284.5 3056.27   304.3 3057.09   312.1 3055.83
   324.1 3054.12   332.6 3054.33   337.73055.954   341.7 3057.41     395 3056.41
   411.2 3058.06   439.1 3058.04   473.9 3059.69   597.7 3062.65     675  3066.9
#Mann= 4 ,-1,0
       0      .1       0   312.1    .045       0   337.7      .1       0
  855.51     .06       0
Bank Sta=312.1,337.7
XS Rating Curve= 0 ,0
Exp/Cntr(USF)=0,0
Exp/Cntr=0.3,0.1

Type RM Length L Ch R = 1 ,255     ,252,255,260.1
XS GIS Cut Line= 4
2226935.26341792484061.6018650522227102.17263936483917.874479925
2227165.53632527483916.3290241712227596.71848065 483747.87434698
#Sta/Elev= 30
       0 3148.13      17 3140.61    49.7  3121.1    61.9 3117.53    74.7 3110.07
   112.1 3091.88   143.7 3069.46   159.6 3059.99   166.2 3053.03   169.23051.015
   176.8 3049.64     191 3049.66  198.213050.847   202.3 3052.17   222.3 3053.93
   238.5  3050.7   246.3 3050.81   258.3 3048.15   266.3 3049.09   278.3 3054.32
   290.8 3052.01   350.9 3051.04   423.9 3053.15   501.2 3053.59   523.1 3055.11
   545.1 3053.69   685.9 3058.69   694.4 3058.26   715.9 3065.37   746.6 3065.53
#Mann= 7 ,-1,0
       0      .1       0   169.2    .045       0  198.21      .1       0
  343.65     .05       0  413.65      .1       0  443.65     .05       0
  653.65     .06       0
#XS Ineff= 2 , 0
                          279.94         3056.43
Permanent Ineff=
       F       F
Bank Sta=169.2,198.21
XS Rating Curve= 0 ,0
Exp/Cntr(USF)=0,0
Exp/Cntr=0.3,0.1

Type RM Length L Ch R = 1 ,0       ,402.9,402.9,402.9
XS GIS Cut Line= 3
2227040.43780694484237.5778232742227353.76756795484091.597457204
2227769.69004165483944.473057034
#Sta/Elev= 30
       0 3115.53    52.7 3092.66    70.3 3082.63    90.4 3068.67   114.4  3054.1
   136.5 3045.39   144.6 3044.42  169.81  3045.4   176.2 3049.75   198.3 3051.84
   224.8 3049.33   301.1 3046.59   325.2 3045.92   352.5 3047.56   402.7 3047.81
   465.4  3047.1   484.2 3049.17   556.1 3050.74   568.9 3049.56   598.6 3054.56
   645.2 3056.58   662.2 3062.15   704.6 3061.57   716.2 3066.82   721.6 3069.61
   726.4 3069.49   734.3 3067.78   748.7 3068.17     764 3073.38   786.8 3075.09
#Mann= 6 ,-1,0
       0      .1       0   136.5    .045       0  169.81      .1       0
   301.1     .05       0   716.2     .06       0   726.4      .1       0
#XS Ineff= 2 , 0
                          197.73         3052.79
Permanent Ineff=
       F       F
Bank Sta=136.5,169.81
XS Rating Curve= 0 ,0
Exp/Cntr=0.3,0.1
LCMann Table=0

Chan Stop Cuts=-1
Use User Specified Reach Order=0
Composite Channel Slope=5